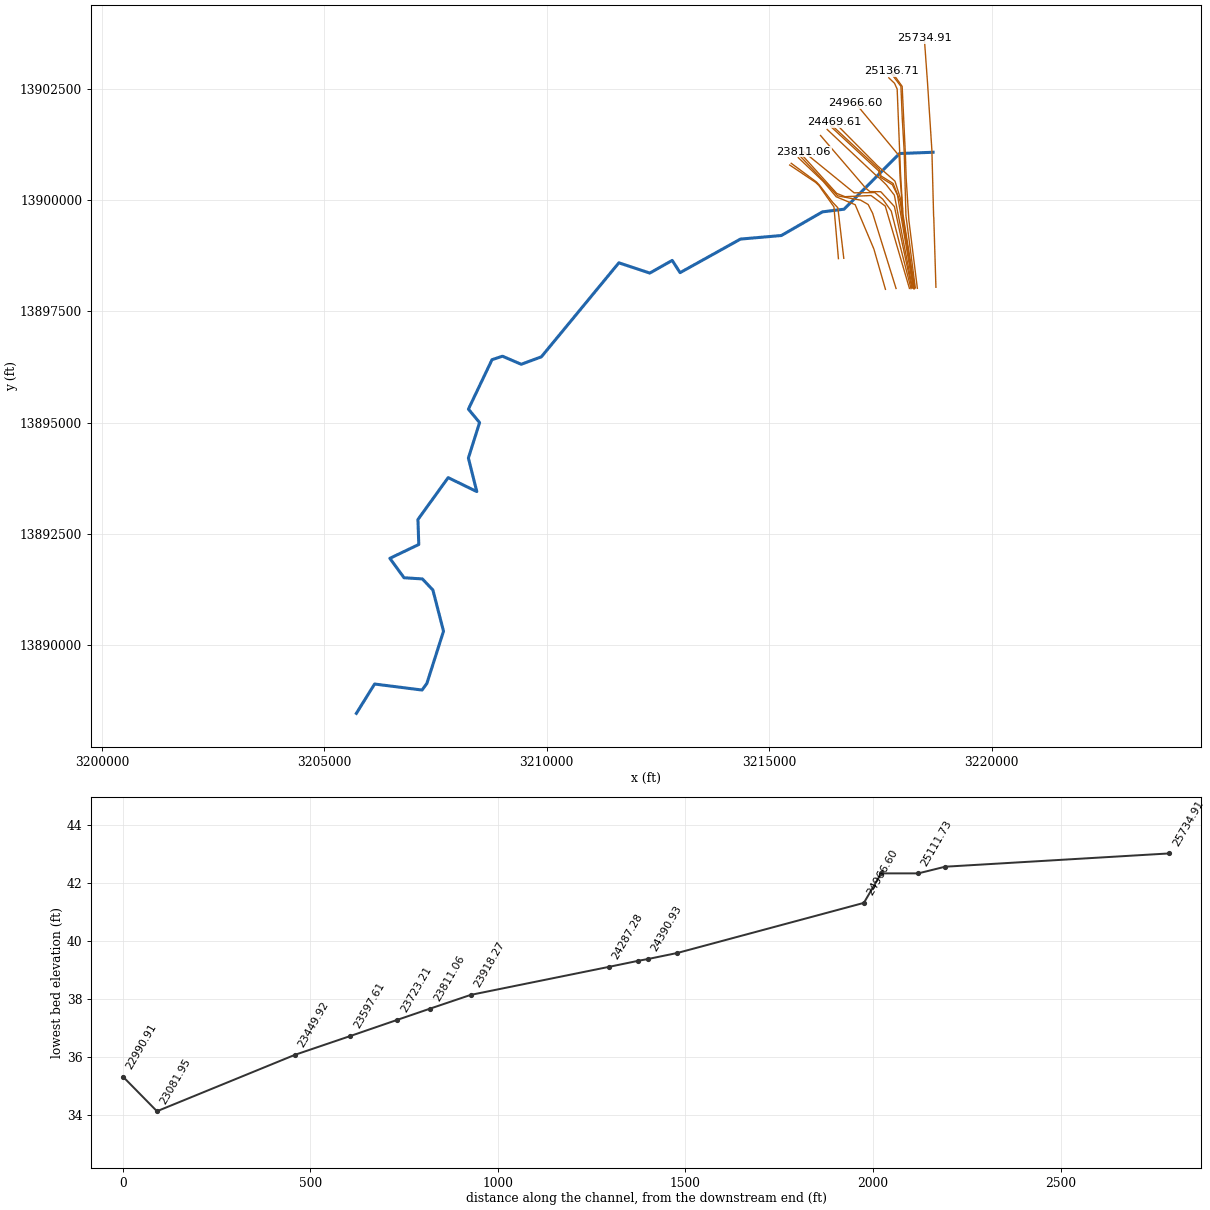
--- R100-00-00.prj (project) ---

Proj Title=R100-00-00
Current Plan=p02
Default Exp/Contr=.3,.1
English Units
Geom File=g01
Flow File=f01
Flow File=f02
Plan File=p01
Plan File=p02
Y Axis Title=Elevation
X Axis Title(PF)=Main Channel Distance
X Axis Title(XS)=Station
BEGIN DESCRIPTION:
Jackson Bayou Watershed     LAN Revised for LOMR OCT2019
Jackson Bayou Watershed
Jackson Bayou
HCFCD unit R 100-00-00
Flood Hazard Model
10, 2, 1, 0.2% Event
Filename R1000000.prj
Prepared by:  FTN Associates Ltd.   DATE:  May 2003
Reviewed by: 	 DATE:
STATUS (FINAL RAS)
normal depth slope calculated between RS 1266.693 and RS 3705.495 with inverts -8.32 and -3.48, respectively. These sections are survey sections, and the normal depth slope calculates to be 0.00198. This value agrees with the average channel slope.
END DESCRIPTION:
DSS Export Rating Curves= 0
DSS Export Rating Curve Sorted= 0
DSS Export Volume Flow Curves= 0
DXF OffsetX= 0
DXF OffsetY= 0
DXF ScaleX= 1
DXF ScaleY= 10

--- R100-00-00.p02 (plan) ---

Plan Title=Effective Floodway 2020
Version=Version 3.0.1  May 2012
Short Identifier=Eff_Floodway
Geom File=g01
Flow File=f02
Subcritical Flow
K Sum by GR= 0
Std Step Tol= 0.01
Critical Tol= 0.01
Num of Std Step Trials= 20
Max Error Tol= 0.3
Flow Tol Ratio= 0.001
Split Flow NTrial= 30
Split Flow Tol= 0.02
Split Flow Ratio= 0.02
Log Output Level= 0
Friction Slope Method= 1
Unsteady Friction Slope Method= 2
Parabolic Critical Depth
Global Vel Dist= 0 , 0 , 0
Global Log Level= 0
CheckData=True
Encroach Param=-1 ,0,0, 2
Encroach River=R100-00-00
Encroach Reach=Jackson Bayou
Encroach Node=25734.91
       1    2809    3183
Encroach Node=25136.71
       1    3001    3094
Encroach Node=25111.73
       1 3014.15 3039.37
Encroach Node=25012.88
       1 3022.56 3047.78
Encroach Node=24966.60
       1    3000    3175
Encroach Node=24469.61
       1    2660    2919
Encroach Node=24390.93
       1    1860    2110
Encroach Node=24378.30
       1    1830    2080
Encroach Node=24365.66
       1    1830    2080
Encroach Node=24287.28
       1    2450    2750
Encroach Node=23918.27
       1    2455    2685
Encroach Node=23811.06
       1    1940    2040
Encroach Node=23767.13
       1    1940    2040
Encroach Node=23723.21
       1    1940    2040
Encroach Node=23597.61
       1    2172    2342
Encroach Node=23449.92
       1 2077.66    2147
Encroach Node=23081.95
       1 1068.05    1132
Encroach Node=22990.91
       1 1072.21 1143.24
Encroach Node=22863.16
       1    1095    1158
Encroach Node=22611.75
       1    1028    1096
Encroach Node=22507.07
       1     999    1068
Encroach Node=22471.50
       1  997.89  1068.7
Encroach Node=22435.93
       1     997    1068
Encroach Node=22331.25
       1     985 1054.55
Encroach Node=21772.21
       1   757.2  854.27
Encroach Node=21719.16
       1     780     856
Encroach Node=21661.92
       1     780     864
Encroach Node=21604.69
       1     813     864
Encroach Node=21550.20
       1  800.06     850
Encroach Node=20899.57
       1     944    1000
Encroach Node=20515.39
       1    1053    1120
Encroach Node=20438.18
       1    1054    1117
Encroach Node=20395.91
       1    1054    1110
Encroach Node=20353.64
       1    1050    1110
Encroach Node=20271.84
       1    1054    1115
Encroach Node=19988.09
       1    1028    1083
Encroach Node=19529.56
       1    1049    1100
Encroach Node=19059.84
       1     421     475
Encroach Node=19004.84
       1    1069    1110
Encroach Node=18980.06
       1    1070    1110
Encroach Node=18955.28
       1    1070    1110
Encroach Node=18902.03
       1  888.17    1015
Encroach Node=18604.81
       1    1160    1275
Encroach Node=17493.69
       1     863    1005
Encroach Node=16435.89
       1    2957    3094
Encroach Node=15606.26
       1    2764    2990
Encroach Node=13644.06
       1    2860    3276
Encroach Node=12489.41
       1    1925    2515
Encroach Node=12099.38
       1    2269    2640
Encroach Node=12087.30
       1    2249    2603
Encroach Node=12070.16
       1    2269    2603
Encroach Node=12053.01
       1    2269    2603
Encroach Node=12032.94
       1    2316    2640
Encroach Node=11826.75
       1    2200    2800
Encroach Node=10282.76
       1    1980    2865
Encroach Node=10011.19
       1    2000    2780
Encroach Node=10001.05
       1    2030    2820
Encroach Node=9975.359
       1    2030    2800
Encroach Node=9949.683
       1    2020    2800
Encroach Node=9939.647
       1    1970    2750
Encroach Node=9552.404
       1    2211    2980
Encroach Node=8173.668
       1     788    2050
Encroach Node=7091.269
       1     960    1680
Encroach Node=6282.693
       1    1435    1830
Encroach Node=6255.746
       1    1435    1830
Encroach Node=6241.746
       1    1435    1830
Encroach Node=6227.747
       1    1435    1830
Encroach Node=6200.685
       1    1419    1830
Encroach Node=5767.792
       1    1243    2170
Encroach Node=5143.828
       1    1100    1800
Encroach Node=3705.495
       1     372    1425
Encroach Node=3104.541
       1     331    1280
Encroach Node=2175.495
       1     135    1215
Encroach Node=1266.693
       1     615    1375
Encroach Node=475.879
       1     680    1000
Encroach Reach=R100-00-00_0005
Encroach Node=25734.91
       1    2809    3183
Encroach Node=25136.71
       1    3001    3094
Encroach Node=25111.73
       1 3014.15 3039.37
Encroach Node=25012.88
       1 3022.56 3047.78
Encroach Node=24966.60
       1    3000    3175
Encroach Node=24469.61
       1    2660    2919
Encroach Node=24390.93
       1    1860    2110
Encroach Node=24378.30
       1    1830    2080
Encroach Node=24365.66
       1    1830    2080
Encroach Node=24287.28
       1    2450    2750
Encroach Node=23918.27
       1    2455    2685
Encroach Node=23811.06
       1    1940    2040
Encroach Node=23767.13
       1    1940    2040
Encroach Node=23723.21
       1    1940    2040
Encroach Node=23597.61
       1    2172    2342
Encroach Node=23449.92
       1 2077.66    2147
Encroach Node=23081.95
       1 1068.05    1132
Encroach Node=22990.91
       1 1072.21 1143.24
Encroach Node=22863.16
       1    1095    1158
Encroach Node=22611.75
       1    1028    1096
Encroach Node=22507.07
       1     999    1068
Encroach Node=22471.50
       1  997.89  1068.7
Encroach Node=22435.93
       1     997    1068
Encroach Node=22331.25
       1     985 1054.55
Encroach Node=21772.21
       1   757.2  854.27
Encroach Node=21719.16
       1     780     856
Encroach Node=21661.92
       1     780     864
Encroach Node=21604.69
       1     813     864
Encroach Node=21550.20
       1  800.06     850
Encroach Node=20899.57
       1     944    1000
Encroach Node=20515.39
       1    1053    1120
Encroach Node=20438.18
       1    1054    1117
Encroach Node=20395.91
       1    1054    1110
Encroach Node=20353.64
       1    1050    1110
Encroach Node=20271.84
       1    1054    1115
Encroach Node=19988.09
       1    1028    1083
Encroach Node=19529.56
       1    1049    1100
Encroach Node=19059.84
       1     421     475
Encroach Node=19004.84
       1    1069    1110
Encroach Node=18980.06
       1    1070    1110
Encroach Node=18955.28
       1    1070    1110
Encroach Node=18902.03
       1  888.17    1015
Encroach Node=18604.81
       1    1160    1275
Encroach Node=17493.69
       1     863    1005
Encroach Node=16435.89
       1    2957    3094
Encroach Node=15606.26
       1    2764    2990
Encroach Node=13644.06
       1    2860    3276
Encroach Node=12489.41
       1    1925    2515
Encroach Node=12099.38
       1    2269    2640
Encroach Node=12087.30
       1    2249    2603
Encroach Node=12070.16
       1    2269    2603
Encroach Node=12053.01
       1    2269    2603
Encroach Node=12032.94
       1    2316    2640
Encroach Node=11826.75
       1    2200    2800
Encroach Node=10282.76
       1    1980    2865
Encroach Node=10011.19
       1    2000    2780
Encroach Node=10001.05
       1    2030    2820
Encroach Node=9975.359
       1    2030    2800
Encroach Node=9949.683
       1    2020    2800
Encroach Node=9939.647
       1    1970    2750
Encroach Node=9552.404
       1    2211    2980
Encroach Node=8173.668
       1     788    2050
Encroach Node=7091.269
       1     960    1680
Encroach Node=6282.693
       1    1435    1830
Encroach Node=6255.746
       1    1435    1830
Encroach Node=6241.746
       1    1435    1830
Encroach Node=6227.747
       1    1435    1830
Encroach Node=6200.685
       1    1419    1830
Encroach Node=5767.792
       1    1243    2170
Encroach Node=5143.828
       1    1100    1800
Encroach Node=3705.495
       1     372    1425
Encroach Node=3104.541
       1     331    1280
Encroach Node=2175.495
       1     135    1215
Encroach Node=1266.693
       1     615    1375
Encroach Node=475.879
       1     680    1000
BEGIN DESCRIPTION:
Update 1:
FEMA effective model modified by LOMR case 20-06-2019P
END DESCRIPTION:
Computation Interval=1HOUR
Output Interval=1HOUR
Run HTab= 0
Run UNet= 0
Run PostProcess= 0
UNET Theta= 1
UNET ZTol= 0.02
UNET ZSATol= 0.1
UNET MxIter= 20
UNET MaxInSteps= 20
UNET DtIC= 0
UNET DtMin= 0
UNET MaxCRTS= 20
UNET WFStab= 2
UNET SFStab= 1
UNET WFX= 1
UNET SFX= 1
UNET Convert EG Bridges=-1
UNET Use Existing IB Tables=-1
Instantaneous Interval=1HOUR
Write IC File= 0
IC Time=0
Write Velocity= 0
Write Detailed= 0

--- R100-00-00.p01 (plan) ---

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Plan Title=Effective Multi-Profile 2020
Short Identifier=Eff_MP
Geom File=g01
Flow File=f01
Encroach Param=-1 ,0,0, 0

--- R100-00-00.f02 (steady flow) ---

Flow Title=Floodway
Version=Version 3.0.1  May 2012
Number of Profiles= 2
Profile Names=1PCT_100yr,1PCTFloodway_100yrFW
River Rch & RM=R100-00-00,R100-00-00_0005 ,25734.91
     771     771
River Rch & RM=R100-00-00,R100-00-00_0005 ,25136.71
     782     782
River Rch & RM=R100-00-00,R100-00-00_0005 ,24966.60
     814     814
River Rch & RM=R100-00-00,R100-00-00_0005 ,24469.61
     851     851
River Rch & RM=R100-00-00,R100-00-00_0005 ,23918.27
     883     883
River Rch & RM=R100-00-00,R100-00-00_0005 ,23449.92
     910     910
River Rch & RM=R100-00-00,R100-00-00_0005 ,23081.95
     945     945
River Rch & RM=R100-00-00,R100-00-00_0005 ,22611.75
     966     966
River Rch & RM=R100-00-00,R100-00-00_0005 ,22331.25
    1011    1011
River Rch & RM=R100-00-00,R100-00-00_0005 ,21772.21
    1029    1029
River Rch & RM=R100-00-00,R100-00-00_0005 ,21550.20
    1084    1084
River Rch & RM=R100-00-00,R100-00-00_0005 ,20899.57
    1125    1125
River Rch & RM=R100-00-00,R100-00-00_0005 ,20438.18
    1166    1166
River Rch & RM=R100-00-00,R100-00-00_0005 ,19988.09
    1210    1210
River Rch & RM=R100-00-00,R100-00-00_0005 ,19529.56
    1273    1273
River Rch & RM=R100-00-00,R100-00-00_0005 ,18902.03
    2623    2623
River Rch & RM=R100-00-00,R100-00-00_0005 ,17493.69
    2722    2722
River Rch & RM=R100-00-00,R100-00-00_0005 ,15606.26
    2829    2829
River Rch & RM=R100-00-00,R100-00-00_0005 ,13644.06
    2894    2894
River Rch & RM=R100-00-00,R100-00-00_0005 ,12489.41
   13588   13588
River Rch & RM=R100-00-00,R100-00-00_0005 ,11826.75
   14114   14114
River Rch & RM=R100-00-00,R100-00-00_0005 ,10282.76
   14740   14740
River Rch & RM=R100-00-00,R100-00-00_0005 ,1266.693
   14755   14755
Boundary for River Rch & Prof#=R100-00-00,R100-00-00_0005 , 1
Up Type= 0
Dn Type= 3
Dn Slope=.00198
DSS Import GetInterval= 0
DSS Import GetPeak= 0
DSS Import FillOption= 0

--- R100-00-00.f01 (steady flow) ---

Flow Title=FEMA Effective June 2007
Version=Version 3.0.1  Mar 2001
Number of Profiles= 4
Profile Names=10PCT_10yr,2PCT_50yr,1PCT_100yr,0.2PCT_500yr
River Rch & RM=R100-00-00,R100-00-00_0005 ,25734.91
     450     662     771    1091
River Rch & RM=R100-00-00,R100-00-00_0005 ,25136.71
     456     671     782    1106
River Rch & RM=R100-00-00,R100-00-00_0005 ,24966.60
     475     698     814    1151
River Rch & RM=R100-00-00,R100-00-00_0005 ,24469.61
     497     730     851    1203
River Rch & RM=R100-00-00,R100-00-00_0005 ,23918.27
     516     758     883    1249
River Rch & RM=R100-00-00,R100-00-00_0005 ,23449.92
     531     780     910    1287
River Rch & RM=R100-00-00,R100-00-00_0005 ,23081.95
     551     810     945    1336
River Rch & RM=R100-00-00,R100-00-00_0005 ,22611.75
     564     829     966    1367
River Rch & RM=R100-00-00,R100-00-00_0005 ,22331.25
     590     867    1011    1430
River Rch & RM=R100-00-00,R100-00-00_0005 ,21772.21
     601     882    1029    1455
River Rch & RM=R100-00-00,R100-00-00_0005 ,21550.20
     633     930    1084    1533
River Rch & RM=R100-00-00,R100-00-00_0005 ,20899.57
     657     965    1125    1591
River Rch & RM=R100-00-00,R100-00-00_0005 ,20438.18
     681    1000    1166    1650
River Rch & RM=R100-00-00,R100-00-00_0005 ,19988.09
     706    1038    1210    1712
River Rch & RM=R100-00-00,R100-00-00_0005 ,19529.56
     743    1092    1273    1800
River Rch & RM=R100-00-00,R100-00-00_0005 ,18902.03
    1524    2247    2623    3701
River Rch & RM=R100-00-00,R100-00-00_0005 ,17493.69
    1573    2327    2722    3847
River Rch & RM=R100-00-00,R100-00-00_0005 ,15606.26
    1626    2413    2829    4004
River Rch & RM=R100-00-00,R100-00-00_0005 ,13644.06
    1658    2465    2894    4099
River Rch & RM=R100-00-00,R100-00-00_0005 ,12489.41
    7653   11599   13588   19603
River Rch & RM=R100-00-00,R100-00-00_0005 ,11826.75
    7913   12033   14114   20353
River Rch & RM=R100-00-00,R100-00-00_0005 ,10282.76
    8174   12533   14740   21277
River Rch & RM=R100-00-00,R100-00-00_0005 ,1266.693
    8177   12543   14755   21303
Boundary for River Rch & Prof#=R100-00-00,R100-00-00_0005 , 1
Up Type= 0
Dn Type= 3
Dn Slope=.00198
DSS Import GetInterval= 0
DSS Import GetPeak= 0
DSS Import FillOption= 0

--- R100-00-00.g01 (geometry) ---

Geom Title=R100-00-00 2020
Version=Version 3.0.1  May 2012

River Reach=R100-00-00      ,R100-00-00_0005
Reach XY= 30
     3218686.071    13901078.252     3217932.242    13901049.806
     3216684.736    13899798.001     3216199.858    13899738.428
     3215275.303    13899206.387     3214356.561    13899126.345
      3212998.17    13898371.168     3212821.846    13898647.254
     3212317.234    13898361.887     3211622.378    13898592.733
     3209880.017    13896479.164     3209426.764    13896311.506
     3209005.357    13896493.084     3208769.872    13896414.202
     3208240.047    13895303.076     3208490.981    13895001.196
     3208239.287    13894204.292     3208428.461    13893449.449
     3207784.494    13893763.116     3207104.883    13892822.116
     3207123.893    13892260.129     3206473.985    13891948.839
     3206792.641    13891511.736     3207205.113    13891486.134
     3207441.218    13891235.806     3207680.168    13890311.298
     3207305.599    13889135.856      3207197.28    13888987.822
     3206130.376    13889123.079     3205720.611    13888463.197

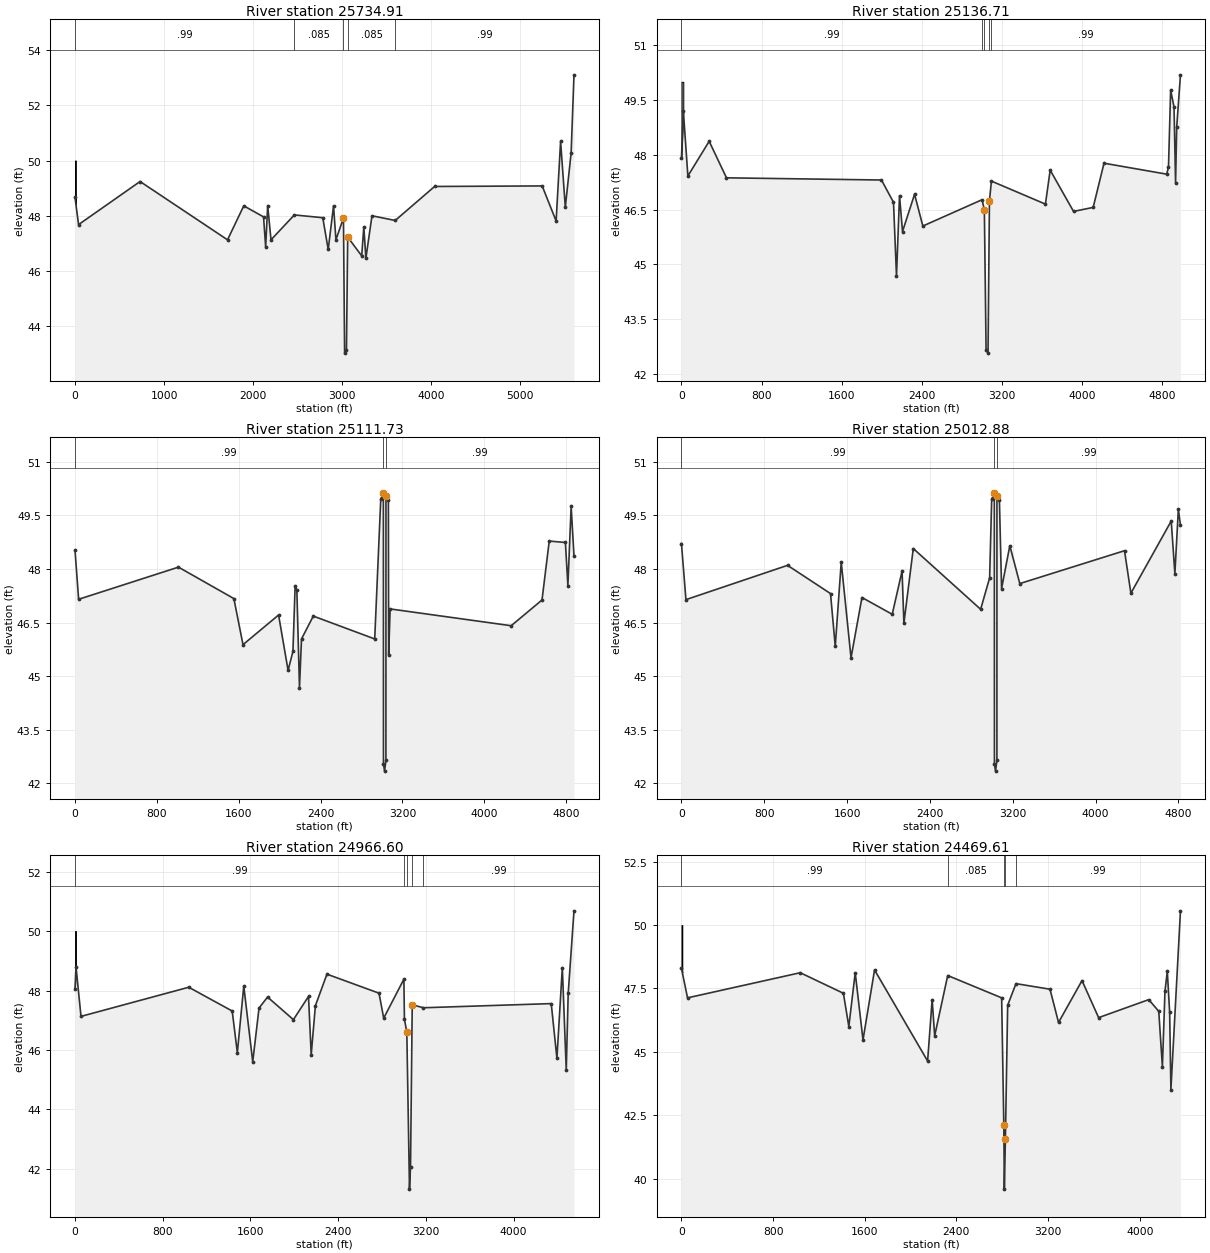
Type RM Length L Ch R = 1 ,25734.91,598.1,598.2,601.63
BEGIN DESCRIPTION:
441v30
Bank Station offset =      1963
Block in left and right overbank at watershed divide.
Set location of n = 0.99 special ineffective area based on ~ 1:1 contraction / expansion ratios from nearest bridge openings and d/s widths of 1% annual chance water surface
END DESCRIPTION:
XS GIS Cut Line= 6
     3218750.343    13898042.981     3218702.333    13899604.531
     3218698.366    13899645.637     3218659.634    13901123.195
     3218560.976    13902644.776      3218489.73    13903639.469
#Sta/Elev= 30
       0   48.67   40.07   47.68  730.93   49.24 1712.97   47.13 1895.45   48.36
 2117.45   47.96 2141.18   46.87 2163.78   48.37  2201.2   47.13 2463.29   48.03
 2782.38   47.93 2843.59   46.78 2903.28   48.36 2930.24   47.13 3014.78   47.92
  3027.7   43.03 3048.48   43.16  3062.5   47.23 3219.63   46.55 3243.46    47.6
 3266.59   46.46 3335.02      48 3595.83   47.83 4038.37   49.06  5246.3   49.08
 5402.93   47.81 5453.17   50.69 5506.12   48.31 5571.33   50.27 5603.68    53.1
#Mann= 5 ,-1 , 0
       0     .99       0 2463.29    .085       0 3014.78    .045       0
  3062.5    .085       0 3595.83     .99       0
#Block Obstruct= 2 , 0
       0   10.05      50 5445.03       0   50.62
Bank Sta=3014.78,3062.5
XS Rating Curve= 0
Exp/Cntr=.3,.1

Type RM Length L Ch R = 1 ,25136.71,71.95,71.5,71.4
BEGIN DESCRIPTION:
441v29
Bank Station offset =      1950
Block in left and right overbank at watershed divide.
Set location of n = 0.99 special ineffective area based on ~ 1:1 contraction / expansion ratios from nearest bridge openings and d/s widths of 1% annual chance water surface
END DESCRIPTION:
XS GIS Cut Line= 6
     3218332.986    13898019.534      3218141.97    13899552.956
      3218081.67    13900491.363     3218064.949    13901008.138
     3217991.144    13902559.709      3217743.38    13902905.355
#Sta/Elev= 30
       0    47.9   18.64   49.21   64.04   47.42  276.63   48.37  449.43   47.37
 1996.56   47.31  2116.6    46.7 2146.59   44.68 2176.65   46.88 2206.71    45.9
 2326.86   46.92  2409.6   46.05 3000.28   46.77 3023.63    46.5 3040.81   42.66
  3060.3   42.57 3074.48   46.74 3094.18   47.28 3633.29   46.65 3680.71   47.58
 3913.85   46.45 4109.96   46.56 4218.11   47.77 4843.97   47.47 4861.64   47.66
 4883.21   49.77 4916.89   49.31 4932.43   47.23 4943.76   48.76 4981.26   50.19
#Mann= 5 ,-1 , 0
       0     .99       0 3000.28    .085       0 3023.63    .045       0
 3074.48    .085       0 3094.18     .99       0
#Block Obstruct= 2 , 0
       0   18.64      50 4883.21       0      50
Bank Sta=3023.63,3074.48
XS Rating Curve= 0
Exp/Cntr=.3,.1

Type RM Length L Ch R = 1 ,25111.73,95.52,98.84,100.61
BEGIN DESCRIPTION:
441v28 use here
Bank Station offset =      1974
Upstream end of concrete channel, n 0.015 due to concrete in channel
(more below)
Set location of n = 0.99 special ineffective area based on ~ 1:1 contraction / expansion ratios from nearest bridge openings and d/s widths of 1% annual chance water surface
END DESCRIPTION:
XS GIS Cut Line= 6
     3218286.286    13898032.774     3218075.716    13899658.841
     3218037.348    13901084.253     3217993.945    13901829.045
     3217963.224    13902560.729     3217762.134     13902826.32
#Sta/Elev= 30
       0   48.53   35.58   47.15 1011.24   48.05 1552.86   47.17 1642.07   45.88
 1989.86   46.71 2082.76   45.16 2130.19   45.69 2151.44   47.51 2168.58    47.4
 2194.13   44.68 2213.93   46.04 2329.18   46.68 2929.42   46.04 2988.54   49.95
 3014.15   50.13 3015.08   42.54 3025.57   42.34    3039   42.64 3039.37   50.05
 3063.22   49.92 3065.64    45.6 3080.18   46.88 4263.32   46.41  4564.6   47.13
 4635.26   48.78 4793.21   48.74 4817.52   47.53  4849.4   49.75 4877.26   48.36
#Mann= 3 ,-1 , 0
       0     .99       0 3014.15    .015       0 3039.37     .99       0
#Block Obstruct= 2 , 0
       0                 4710.21       0      50
Bank Sta=3014.15,3039.37
XS Rating Curve= 0
Exp/Cntr=.5,.3

Type RM Length L Ch R = 1 ,25012.88,15,46.28,68
BEGIN DESCRIPTION:
441v28 use here
Bank Station offset =      1966
Downstream end of concrete channel,  Hence n 0.015 not used at this section as the concrete lining does not extend to the next d/s section.
(more below)
Set location of n = 0.99 special ineffective area based on ~ 1:1 contraction / expansion ratios from nearest bridge openings and d/s widths of 1% annual chance water surface
Block in right overbank at watershed divide.
END DESCRIPTION:
XS GIS Cut Line= 6
     3218272.169    13898025.172     3218008.654    13899690.527
     3217955.636    13900576.389     3217878.829    13902499.033
     3217820.161    13902628.473     3217691.126    13902751.498
#Sta/Elev= 30
       0   48.71   43.21   47.14 1024.99    48.1 1439.94   47.31 1485.83   45.83
 1543.48   48.19 1638.08   45.51 1743.78    47.2 2036.05   46.73 2131.25   47.94
 2148.92   46.48 2239.52   48.57 2890.26   46.87 2977.11   47.75 2996.95   49.95
 3022.56   50.13 3023.49   42.54 3033.98   42.34 3047.41   42.64 3047.78   50.05
 3071.63   49.92 3092.61   47.45  3172.1   48.65 3268.68   47.59 4280.02   48.51
 4341.75   47.32 4731.44   49.34 4766.64   47.87 4800.35   49.67 4820.68   49.22
#Mann= 3 ,-1 , 0
       0     .99       0 3022.56    .045       0 3047.78     .99       0
#Block Obstruct= 2 , 0
       0                 4731.21       0      50
Bank Sta=3022.56,3047.78
XS Rating Curve= 0
Exp/Cntr=.5,.3

Type RM Length L Ch R = 1 ,24966.60,489.35,496.99,505.28
BEGIN DESCRIPTION:
441v27
Bank Station offset =      1946
Set location of n = 0.99 special ineffective area based on ~ 1:1 contraction / expansion ratios from nearest bridge openings and d/s widths of 1% annual chance water surface
 Block in left and right overbank at watershed divide.
END DESCRIPTION:
XS GIS Cut Line= 6
     3218269.252    13898013.945     3217998.741    13899670.144
     3217998.741    13899826.394     3217946.658    13900477.436
     3217922.927    13900999.249     3216938.914    13902183.476
#Sta/Elev= 30
       0   48.06    9.21    48.8    54.8   47.13 1037.46   48.11 1433.61   47.31
 1480.34   45.91 1539.08   48.15 1620.76    45.6 1678.15   47.41 1756.03   47.78
 1991.52   47.02 2129.32    47.8 2153.97   45.84 2192.17   47.49 2297.51   48.55
 2772.34   47.91 2814.96   47.07 2999.03   48.38 3004.07   47.04 3025.94   46.59
 3050.16   41.32 3059.52   42.07 3075.22   47.52 3177.03   47.42 4342.76   47.56
 4394.48   45.72 4443.84   48.77 4479.69   45.32  4497.4    47.9 4550.28   50.68
#Mann= 5 ,-1 , 0
       0     .99       0 2999.03    .085       0 3025.94    .045       0
 3075.22    .085       0 3177.03     .99       0
#Block Obstruct= 2 , 0
       0    9.21      50 4443.84       0      50
Bank Sta=3025.94,3075.22
XS Rating Curve= 0
Exp/Cntr=.5,.3

Type RM Length L Ch R = 1 ,24469.61,101.1,78.69,48.32
BEGIN DESCRIPTION:
441s10 surveyed here Private Drive --xsec 4/4 os
Bank Station offset =      2182
Set location of n = 0.99 special ineffective area based on ~ 1:1 contraction / expansion ratios from nearest bridge openings and d/s widths of 1% annual chance water surface
Block in left and right overbank at watershed divide.
END DESCRIPTION:
XS GIS Cut Line= 6
     3218264.233    13898015.649     3217993.211    13899645.617
     3217963.697     13900003.06     3217829.214    13900429.565
     3217440.558    13900770.306     3216470.916    13901749.125
#Sta/Elev= 30
       0   48.29   53.11   47.13 1036.81   48.12 1413.55   47.31 1460.83      46
 1516.66   48.12 1584.53   45.47 1685.37   48.23 2148.55   44.64 2188.22   47.06
 2210.07   45.63 2323.94   48.01 2794.82   47.13 2813.68    42.1 2818.32   39.59
 2827.48   41.58  2847.3   46.84 2919.81   47.69  3216.8   47.47 3291.27   46.16
 3496.23   47.81 3641.24   46.35 4078.67   47.06 4166.01    46.6 4197.83   44.42
 4220.29   47.39 4240.64   48.18 4261.12   46.56 4272.07   43.51 4355.55   50.56
#Mann= 5 ,-1 , 0
       0     .99       0 2323.94    .085       0 2813.68    .045       0
 2827.48    .085       0 2919.81     .99       0
#Block Obstruct= 2 , 0
       0    7.48      50 4240.64       0      50
Bank Sta=2813.68,2827.48
XS Rating Curve= 0
Exp/Cntr=.5,.3

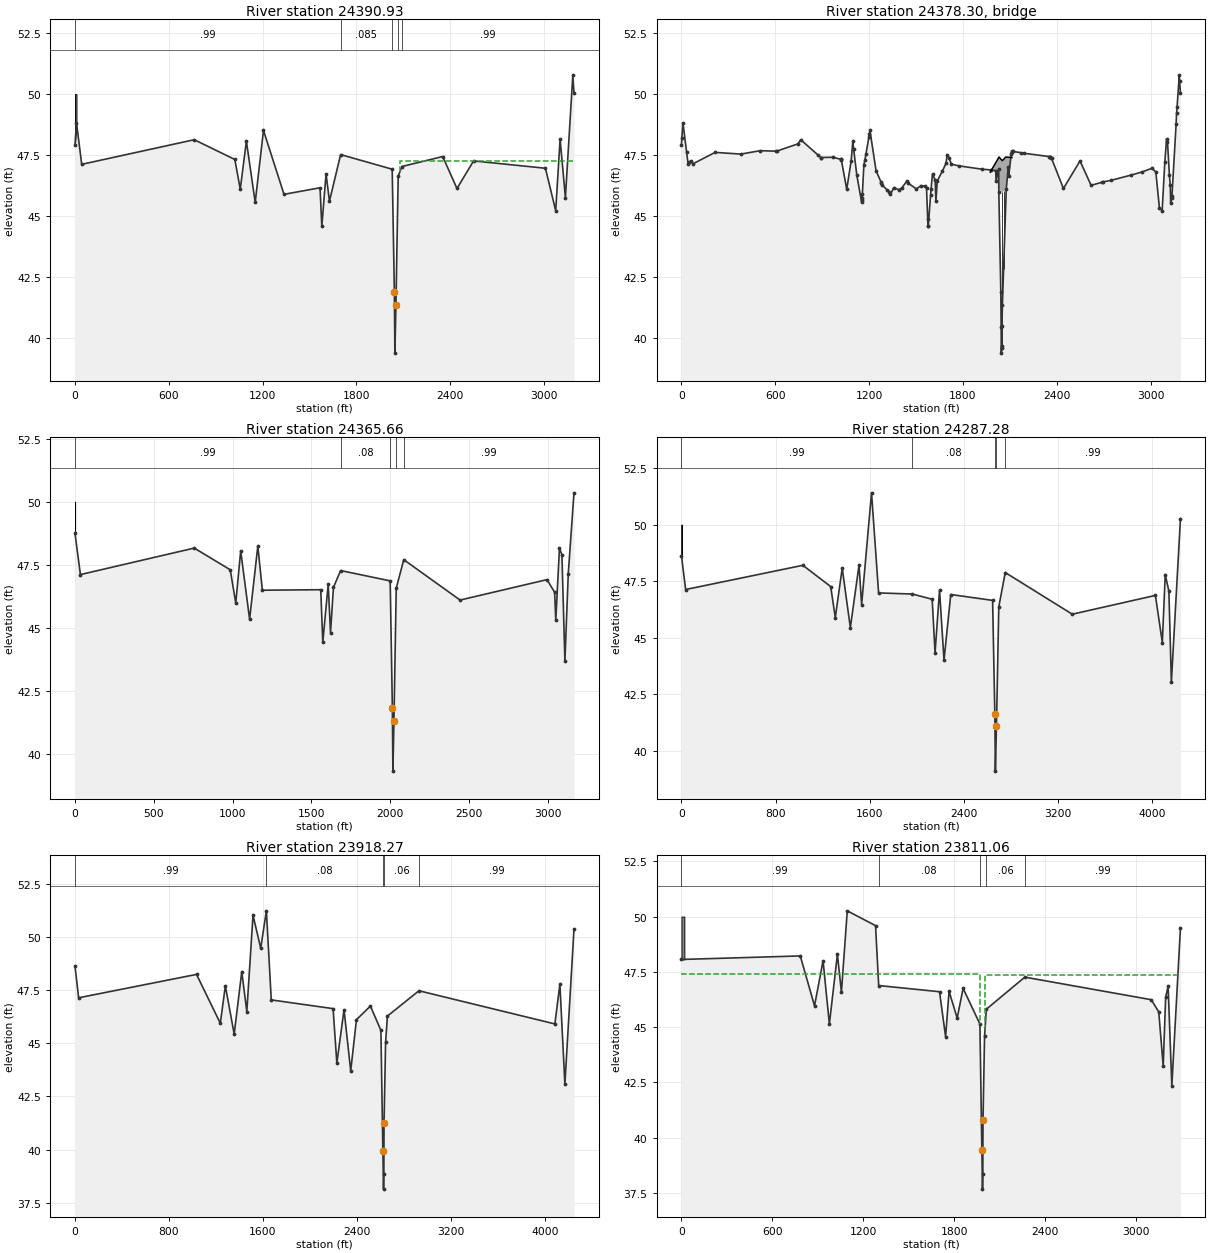
Type RM Length L Ch R = 1 ,24390.93,24.56,25.26,29.14
BEGIN DESCRIPTION:
441s10 copied here Private Drive -- xsec 3/4 os
channel elevations adjusted based on slope between 441s10 and 441s9
Set location of n = 0.99 special ineffective area based on ~ 1:1 contraction / expansion ratios from nearest bridge openings and d/s widths of 1% annual chance water surface
(more below)
Bank Station offset =      2203
Block in left and right overbank at watershed divide.
END DESCRIPTION:
XS GIS Cut Line= 6
     3218253.773    13898010.075     3217948.101    13899967.052
     3217789.263     13900375.72     3217514.955    13900546.759
     3217479.557    13900690.846     3216406.681    13901687.949
#Sta/Elev= 30
       0   47.92   9.603   48.82   42.96   47.12 762.531   48.131022.198   47.32
1056.872    46.11096.065   48.071152.453   45.561205.388   48.511336.688   45.89
1567.115   46.161578.422   44.581605.585   46.731627.262   45.611698.818   47.52
2028.541   46.922042.334   41.892045.728   39.382052.427   41.372066.923   46.63
2090.267   47.032351.492   47.442442.736   46.132548.804   47.263008.445   46.96
3074.077   45.223102.241   48.153136.207   45.763183.765   50.793191.145   50.03
#Mann= 5 ,-1 , 0
       0     .99       01698.818    .085       02028.541     .05       0
2066.923    .085       02090.267     .99       0
#XS Ineff= 2 , 0
       0 2025.85    46.82077.044       0   47.27
Permanent Ineff=
       F       F
#Block Obstruct= 2 , 0
       0   9.603      503102.241       0      50
Bank Sta=2042.334,2052.427
XS Rating Curve= 0
Skew Angle= 43
Exp/Cntr=.5,.3

Type RM Length L Ch R = 3 ,24378.30,,,
BEGIN DESCRIPTION:
441s10, Private Drive
Block at watershed divide
internal section defined to show entire structure in bridge info
0.99 still in on LOB because ineffective station lower thatn 100 yr WSEL
Road ended early as upstream and downstream sections cross the road.
END DESCRIPTION:
Bridge Culvert--1,0,-1,-1, 0
Deck Dist Width WeirC Skew NumUp NumDn MinLoCord MaxHiCord MaxSubmerge Is_Ogee
5.7,13.8,2.6,43, 5, 5, , , .95, 0, 0,0,,
1974.6552030.8452051.7752074.1852113.612
    46.8   47.42   47.27   47.42    47.4
           46.12   45.97   46.09
1956.3712001.0642021.9952044.4042091.672
    46.8   47.42   47.27   47.42    47.7
           46.12   45.97   46.09
Pier Skew, UpSta & Num, DnSta & Num=  ,2047.395, 2 ,2017.615, 2 , 0 , 0 , 0 ,0,
       1       1
      38      48
       1       1
      38      48
Pier Skew, UpSta & Num, DnSta & Num=  ,2060.033, 2 ,2030.253, 2 , 0 , 0 , 0 ,0,
       1       1
      38      48
       1       1
      38      48
BR Coef=-1 , 1 , 1 ,.9, 0 ,,,.8,0,1.2,0,
WSPro=,,,, 1 ,,,, 0 ,,,, 0 ,,,,-1 ,-1 ,-1 , 0 , 0 , 0 , 0 , 0
BR U #Sta/Elev= 121
       0   47.92     2.3   48.21     9.6   48.82   32.92   47.62   42.96   47.12
   47.11    47.2    61.3   47.25   72.81   47.14  215.33   47.61  379.77   47.54
  503.93   47.68  606.31   47.66  608.91   47.66  745.12   47.96  762.53   48.13
  871.91   47.51  891.28    47.4  893.52    47.4  969.48   47.41 1021.88   47.32
  1022.2   47.32 1022.48    47.3 1056.87    46.1 1085.01   47.25 1096.07   48.07
 1101.19   47.74 1121.53   46.67 1152.45   45.56 1154.73   45.66 1156.23   45.75
  1157.1   45.92 1166.66   47.11 1173.32    47.3    1180   47.55 1198.83   48.24
 1201.93   48.38 1205.39   48.51 1244.49   46.86 1276.44   46.39 1278.15   46.37
 1282.14   46.28 1314.42   46.08 1329.63   45.97 1336.69   45.89 1358.15   46.17
 1388.07   46.08 1407.42   46.14 1440.03   46.42 1449.57   46.35 1502.57   46.11
  1532.4   46.25 1557.89   46.22 1567.12   46.16 1574.86   44.86 1578.42   44.58
 1578.73   44.61 1593.06   45.86 1596.34   46.12 1605.59   46.73 1622.44   46.47
 1627.26   45.61 1635.88   46.44 1667.63   46.83 1691.92   47.16 1698.82   47.52
  1709.7    47.4  1726.5   47.13 1771.97   47.06 1923.64   46.92 1980.07   46.89
 2010.16   46.86 2011.73   46.44 2028.54   46.92 2029.51      46 2042.33   41.89
 2044.35   40.44 2045.73   39.38  2047.4    39.6 2048.34   39.69 2049.71   40.49
 2052.43   41.37 2077.04   46.09 2090.27   47.03 2092.48   46.65  2109.2   47.54
 2110.71   47.62 2114.56   47.65 2119.78   47.65 2168.58    47.6 2193.71   47.57
 2351.49   47.44 2359.32   47.41 2359.82   47.41  2360.3    47.4 2366.86   47.36
 2442.74   46.13  2548.8   47.26 2619.61   46.26 2686.57   46.38 2695.46    46.4
 2744.54   46.46 2875.88   46.68 2946.86   46.81 3008.45   46.96 3033.52   46.81
  3056.8   45.32 3074.08   45.22 3091.15   47.21 3102.24   48.15  3108.1   48.05
 3120.54   46.67 3125.89   46.26 3128.44   45.53 3135.62   45.82 3136.21   45.76
 3163.43   48.78 3166.24   49.21 3169.48   49.47 3183.77   50.79 3185.79   50.52
 3191.15   50.03
BR U #Mann= 5
       0     .99 1698.82    .085 2028.54     .05 2077.04    .085 2119.78     .99
BR U Banks=2042.33,2052.43
BR D #Sta/Elev= 118
       0   48.74       1   48.83   33.52   47.15   34.43   47.11   34.81   47.12
   36.03   47.12   36.99   47.11  191.61   47.64  379.97   47.57  493.89    47.7
  588.26   47.68  601.36   47.71  743.38   48.03  756.41   48.16  854.56   47.61
  869.84   47.52  899.63   47.35  949.67   47.36   984.8    47.3 1007.29    46.3
 1019.62   45.98 1036.95   46.97 1038.87   47.15 1047.45   47.95 1051.04   48.05
 1065.24   47.85 1069.29   47.71 1072.33   47.52 1093.63   46.13    1103   45.53
 1104.77   45.43 1107.44   45.34 1137.92   46.81 1158.19   47.96  1159.6   48.24
 1169.01   47.78  1176.1   47.42 1188.43   46.49 1191.89   46.86 1193.88   46.82
 1227.79   47.32 1235.26   46.47 1260.16   46.47 1299.67    46.2 1316.08   46.03
 1333.12   46.29 1373.28   46.96 1376.54   46.95 1385.89   46.95 1391.16   46.94
 1394.93   46.94 1511.34    46.3 1557.65   46.51 1558.73   46.51 1566.74   45.24
 1571.66   44.43  1573.3   44.56 1605.99   46.72 1610.36   46.65 1620.71   44.81
 1639.33    46.6 1651.14   46.74 1682.93   47.18 1684.68   47.27 1687.43   47.24
 1691.64   47.17 1743.47    47.1 1864.35   46.98 1885.39   46.97 1977.39   46.88
 1982.36   46.38 1999.17   46.86 2000.25      46 2012.96   41.83 2014.97   40.38
 2016.36   39.32 2018.02   39.54 2018.97   39.63 2020.34   40.43 2023.06   41.31
 2047.79   46.09  2060.9   46.97 2068.19   46.64 2082.71   47.24  2085.3    47.7
 2088.48   47.69 2271.71   47.54 2330.67   47.31 2334.53   47.33  2338.2    47.3
 2389.06   46.97 2442.47    46.1 2516.08   46.89 2564.54   46.19 2671.98    46.4
 2762.86   46.51 2787.91   46.56 2978.28   46.88 2986.82   46.89 2993.85   46.91
 2996.61   46.89 2999.14   46.73 3010.57   46.67 3042.08   46.41 3049.49    45.3
  3069.1   47.59 3071.44   47.92  3072.8   48.15 3074.35   48.13 3088.35    47.9
 3090.85   47.27 3103.89   43.69 3107.37   43.68 3111.65   43.96 3123.88   46.41
 3128.72   47.15 3139.26   48.01 3165.04   50.35
BR D #Mann= 5
       0     .99 1684.68     .08 2000.25     .05 2047.79     .08  2085.3     .99
BR D Banks=2012.96,2023.06
BC Design=,, 0 ,, 0 ,,,,,,
BC HTab HWMax=50.79

Type RM Length L Ch R = 1 ,24365.66,58.03,78.38,104.82
BEGIN DESCRIPTION:
Private Drive -- xsec 2/4 os 441s10
channel elevations adjusted based on slope between 441s10 and 441s9
Set location of n = 0.99 special ineffective area based on ~ 1:1 contraction / expansion ratios from nearest bridge openings and d/s widths of 1% annual chance water surface
(more below)
Bank Station offset =      2243
Block in left and right overbank at watershed divide.
Adjusted ineffective flow heights to remove a negative WS
END DESCRIPTION:
XS GIS Cut Line= 6
     3218242.164    13898021.685     3217884.439    13900120.902
      3217770.91     13900348.19      3217501.93    13900516.582
      3217461.97    13900660.189      3216382.21    13901660.419
#Sta/Elev= 30
       0   48.74  34.432   47.11  756.41   48.16 984.797    47.31019.624   45.98
1051.043   48.051107.438   45.341159.598   48.241188.428   46.491558.727   46.51
1571.657   44.431605.987   46.721620.709   44.811639.329    46.61684.681   47.27
 1999.17   46.862012.963   41.832016.357   39.322023.056   41.312037.551   46.57
2085.302    47.72442.465    46.12993.848   46.91 3042.08   46.413049.489    45.3
3072.804   48.153088.346    47.93107.368   43.683128.717   47.153165.043   50.35
#Mann= 5 ,-1 , 0
       0     .99       01684.681     .08       0 1999.17     .05       0
2037.551     .08       02085.302     .99       0
#XS Ineff= 2 , 0
       0    1997    46.6    2047       0    46.6
Permanent Ineff=
       F       F
#Block Obstruct= 2 , 0
       0   1.002      503072.804       0      50
Bank Sta=2012.963,2023.056
XS Rating Curve= 0
Skew Angle= 43
Exp/Cntr=.5,.3

Type RM Length L Ch R = 1 ,24287.28,373.53,369.01,368.7
BEGIN DESCRIPTION:
441s10 Private Drive -- xsec 1/4 os
channel elevations adjusted based on slope between 441s10 and 441s9
Bank Station offset =      2333
(more below)
Set location of n = 0.99 special ineffective area based on ~ 1:1 contraction / expansion ratios from nearest bridge
openings and d/s widths of 1% annual chance water surface
Block in left and right overbank at watershed divide.
END DESCRIPTION:
XS GIS Cut Line= 6
     3218222.785    13898028.913     3217815.472    13900115.597
     3217633.263     13900348.19      3217486.44    13900491.954
     3217413.029    13900550.072      3216305.74    13901590.067
#Sta/Elev= 30
       0   48.62   35.55   47.13 1031.69    48.2 1267.94   47.26 1306.92   45.89
 1365.89   48.07 1434.98   45.45 1508.79   48.21 1530.77   46.46 1614.93    51.4
 1674.95   46.98 1962.12   46.93 2130.28    46.7 2154.59   44.33 2192.67    47.1
 2230.78   44.01 2288.04   46.91 2643.72   46.65 2662.58   41.62 2667.22   39.11
 2676.38    41.1  2696.2   46.36 2751.03   47.88 3320.65   46.04 4027.02   46.87
 4085.55   44.79 4110.49   47.79 4141.33   47.06 4162.55   43.04 4239.78   50.26
#Mann= 5 ,-1 , 0
       0     .99       0 1962.12     .08       0 2662.58     .05       0
 2676.38     .08       0 2751.03     .99       0
#Block Obstruct= 2 , 0
       0       2      50 4110.49       0      50
Bank Sta=2662.58,2676.38
XS Rating Curve= 0
Exp/Cntr=.3,.1

Type RM Length L Ch R = 1 ,23918.27,87.15,107.21,117.16
BEGIN DESCRIPTION:
441s9u; xs 4/4 Runneburg (survey here)
Set location of n = 0.99 special ineffective area based on ~ 1:1 contraction / expansion ratios from nearest bridge openings and d/s widths of 1% annual chance water surface
Bank Station offset =      2373
Block in left and right overbank at watershed divide.
END DESCRIPTION:
XS GIS Cut Line= 6
     3218207.074    13898029.519     3217816.449    13899858.946
      3217510.46    13900190.977      3217265.84    13900194.504
     3217171.656    13900271.322     3216155.858    13901455.479
#Sta/Elev= 30
       0   48.62   31.12   47.14 1034.99   48.24 1237.41   45.94 1280.41    47.7
 1355.64   45.43 1420.13   48.37 1463.13   46.49 1515.91   51.02 1581.54   49.47
 1629.66   51.23  1671.4   47.04 2197.81   46.63 2229.79   44.07 2290.99   46.58
 2347.88    43.7  2396.7   46.11 2515.43   46.75 2604.94   45.61 2621.77   39.91
 2627.21   38.14 2630.17   38.83 2631.68   41.25 2644.92   45.05 2660.33   46.28
 2928.74   47.47 4086.49   45.91 4129.04   47.78 4171.59   43.08 4249.22   50.37
#Mann= 5 ,-1 , 0
       0     .99       0 1629.66     .08       0 2621.77     .05       0
 2631.68     .06       0 2928.74     .99       0
#Block Obstruct= 2 , 0
       0       0      50 4129.04       0      50
Bank Sta=2621.77,2631.68
XS Rating Curve= 0
Exp/Cntr=.5,.3

Type RM Length L Ch R = 1 ,23811.06,86.42,87.85,109.89
BEGIN DESCRIPTION:
copy of 441s9u; xs 3/4 Runneburg
channel elevations adjusted based on slope between 441s9 and 441s8  Set location of n = 0.99 special ineffective area based on ~ 1:1 contraction / expansion ratios from nearest bridge openings and d/s widths of 1% annual chance water surface (more below)
Bank Station offset =      2408
Block in left and right overbank at watershed divide.
END DESCRIPTION:
XS GIS Cut Line= 6
      3218189.96      13898012.5     3217746.505    13899754.845
     3217556.033    13900021.706     3217379.256    13900171.788
     3216911.626    13900166.287     3215778.643    13901088.854
#Sta/Elev= 30
       0   48.06 783.686   48.22 877.527   45.96 933.877      48 975.496   45.14
1028.453   48.291054.935   46.58 1093.49   50.261279.961   49.591300.759   46.88
1701.974    46.61742.031   44.561764.722   46.621818.344   45.411857.635   46.75
 1968.25   45.141981.144   39.441985.312   37.67 1987.58   38.361988.735   40.78
1998.878   44.582010.683   45.812264.419   47.263097.985   46.243147.667   45.69
3177.039   43.24 3193.31   46.353209.572   46.853233.972   42.343290.933   49.49
#Mann= 5 ,-1 , 0
       0     .99       01300.759     .08       0 1968.25    .035       0
2010.683     .06       02264.419     .99       0
#XS Ineff= 2 , 0
       01967.968    47.42001.674       0   47.34
Permanent Ineff=
       F       F
#Block Obstruct= 2 , 0
       0  19.136      503209.572       0      50
Bank Sta=1981.144,1988.735
XS Rating Curve= 0
Skew Angle= 40
Exp/Cntr=.5,.3

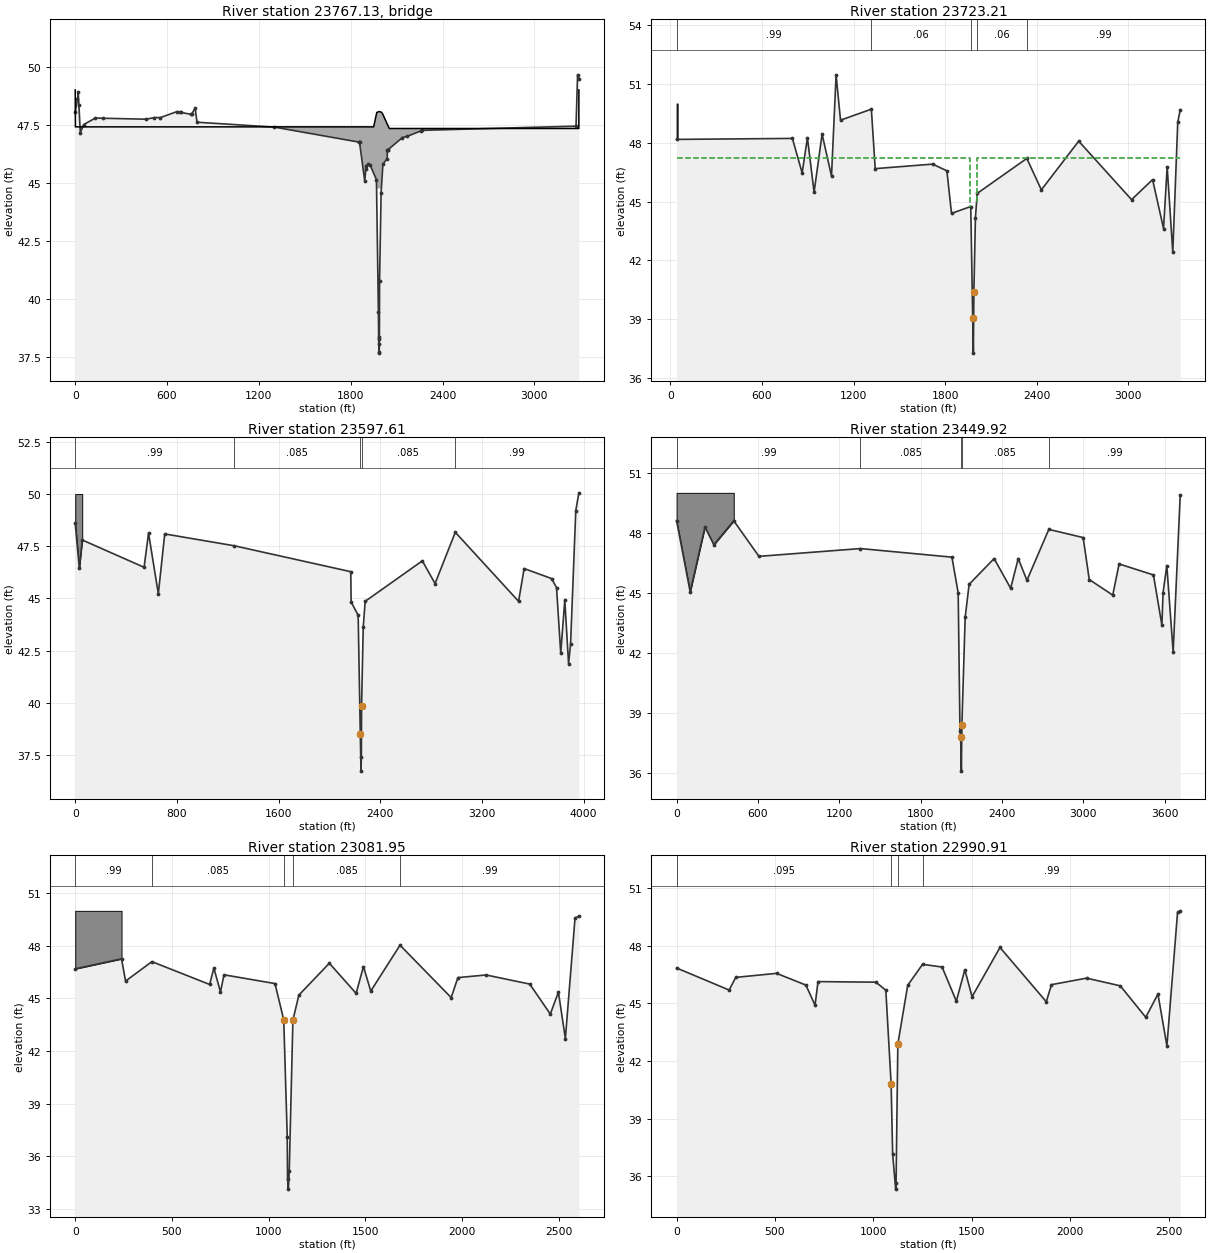
Type RM Length L Ch R = 3 ,23767.13,,,
BEGIN DESCRIPTION:
441s9, concrete bridge, Runneburg Rd
Added 0.5 ft to TOR to get high chord based on curb height indicated in survey notes. Subtracted 2.80 ft from TOR (from survey) to get low chord.
Road ended early as upstream and downstream sections cross the road - continued roadway to correspond to edges of internal sections with road at elevations recorded for LOB and ROB to remove crossings from storage-routing model.
END DESCRIPTION:
Bridge Culvert--1,0,-1,-1, 0
Deck Dist Width WeirC Skew NumUp NumDn MinLoCord MaxHiCord MaxSubmerge Is_Ogee
24.69,36,2.6,40, 14, 14, , , .95, 0, 0,0,,
       0    1.08 1950.03 1970.53 1970.54 1971.47 1984.25 1998.11 1998.85 1998.86
 2007.32 2052.26 3290.94 3291.22
      49   47.41   47.41   48.03   48.03   48.03   48.07   48.05   48.05   48.05
   47.99   47.34   47.34      49
                                   44.73   44.73   44.77   44.75   44.75
                                
       0   40.58  1961.8 1970.53 1970.54 1971.47 1984.25 1998.11 1998.85 1998.86
 2007.32 2054.87 3331.52 3336.72
      49   47.41   47.41   48.03   48.03   48.03   48.07   48.05   48.05   48.05
   47.99   47.34   47.34      49
                                   44.73   44.73   44.77   44.75   44.75
                                
BR Coef=-1 , 1 , 0 ,, 0 ,,,.7,0,0,0,
WSPro=,,,, 1 ,,,, 0 ,,,, 0 ,,,,-1 ,-1 ,-1 , 0 , 0 , 0 , 0 , 0
BR U #Sta/Elev= 48
       0   48.06  14.679   48.61  19.133   48.91  24.115   48.34  33.302   47.16
  55.392   47.51 131.973   47.79 182.458   47.78 463.609   47.74 517.831   47.81
 556.886   47.81 665.849   48.07  686.41   48.04 691.091   48.03 756.915   47.95
 760.014   47.95 783.685   48.22 795.916   47.611300.757    47.41857.284   46.75
1857.449   46.751857.632   46.751891.985   45.07 1900.75   45.741902.083   45.58
1910.174   45.791925.948   45.781968.252   45.141981.145   39.441982.834   38.29
1983.355   38.051985.315   37.671986.399    37.7 1987.58   38.361988.739   40.78
1998.878   44.582010.688   45.812038.347   46.042039.634    46.42041.866   46.41
2042.863   46.422138.166   46.952169.225      472260.541   47.242264.419   47.26
  3272.4   47.443282.768   49.653290.936   49.49
BR U #Mann= 5
       0     .991300.757     .081968.252    .0351998.878     .06  3272.4     .99
BR U Banks=1981.145,1988.739
BR D #Sta/Elev= 28
  40.582   48.17  47.721   48.65  51.633    48.2  69.074    47.41317.019   49.71
 1889.98   44.461901.496   43.991917.672   44.27 1920.65   44.32 1925.98   45.39
1968.296   44.751981.188   39.051982.868    37.91983.398   37.661985.359   37.28
1986.443   37.311987.623   37.971988.782   40.391998.922   44.19 2010.72   45.42
2038.388   45.652039.495   47.342335.595    47.22677.424   48.053324.651   49.05
3339.047   49.553340.912   49.683340.934   49.68
BR D #Mann= 5
  40.582     .991317.019     .061968.296    .0352038.388     .062335.595     .99
BC Design=,, 0 ,, 0 ,,,,,,
BC HTab HWMax=50.26

Type RM Length L Ch R = 1 ,23723.21,134.38,125.6,125.5
BEGIN DESCRIPTION:
copy of 441s9u; xs 2/4 Runneburg
channel elevations adjusted based on slope between 441s9 and 441s8  Set location of n = 0.99 special ineffective area based on ~ 1:1 contraction / expansion ratios from nearest bridge openings and d/s widths of 1% annual chance water surface (more below)
Bank Station offset =      2461
Block in left and right overbank at watershed divide.
END DESCRIPTION:
XS GIS Cut Line= 6
     3218154.789    13898017.189     3217611.337    13899868.567
     3217291.667     13900105.36     3216706.369    13900079.682
     3216519.317    13900153.952      3215724.44    13901034.651
#Sta/Elev= 30
  40.582   48.17 799.664   48.22 863.419   46.46 898.076   48.25 941.691   45.48
  994.19   48.441055.834    46.31085.907   51.461114.876   49.151317.019   49.71
1342.282   46.681718.292   46.911811.903   46.571842.183    44.41968.296   44.75
1981.188   39.051985.359   37.281988.782   40.391998.922   44.19 2010.72   45.42
2335.595    47.22430.918    45.62675.649   48.083022.115    45.13159.776   46.12
3231.558   43.633255.305   46.773292.151   42.423324.651   49.053340.934   49.68
#Mann= 5 ,-1 , 0
  40.582     .99       01317.019     .06       01968.296    .035       0
 2010.72     .06       02335.595     .99       0
#XS Ineff= 2 , 0
       0 1963.08    47.2 2006.34       0    47.2
Permanent Ineff=
       F       F
#Block Obstruct= 2 , 0
  40.582  47.721      503255.305  40.582      50
Bank Sta=1981.188,1988.782
XS Rating Curve= 0
Skew Angle= 40
Exp/Cntr=.4,.2

Type RM Length L Ch R = 1 ,23597.61,152.49,147.69,126.15
BEGIN DESCRIPTION:
copy of 441s9u; xs 1/4 Runneburg
channel elevations adjusted based on slope between 441s9 and 441s8  Set location of n = 0.99 special ineffective area based on ~ 1:1 contraction / expansion ratios from nearest bridge openings and d/s widths of 1% annual chance water surface  (more below)
Bank Station offset =      2751
Block in right overbank at watershed divide. LOB block at watershed divide.
END DESCRIPTION:
XS GIS Cut Line= 6
     3217854.049    13898015.667     3217327.426    13899706.274
     3217226.549    13899904.086     3217058.329    13900001.413
     3216542.259    13900097.859     3215687.176    13901004.162
#Sta/Elev= 30
       0   48.59   32.15   46.45   55.21    47.8  541.95   46.49   576.9   48.13
  654.04   45.22  704.34   48.09 1253.38   47.52 2168.43   46.28 2171.34   44.83
 2226.57   44.19  2243.4   38.49 2248.84   36.72  2251.8   37.41 2253.31   39.83
 2266.55   43.63 2281.96   44.86 2731.58    46.8 2831.65   45.71 2990.92   48.17
 3489.01   44.86 3532.73   46.43 3748.94   45.95 3787.55   45.52 3820.84   42.37
 3852.67   44.92 3882.45   41.87 3898.12   42.81 3939.13   49.21 3963.61   50.06
#Mann= 5 ,-1 , 0
       0     .99       0 1253.38    .085       0  2243.4    .045       0
 2253.31    .085       0 2990.92     .99       0
#Block Obstruct= 2 , 0
       0   55.21      50 3852.67       0      50
Bank Sta=2243.4,2253.31
XS Rating Curve= 0
Exp/Cntr=.3,.1

Type RM Length L Ch R = 1 ,23449.92,403.6,367.97,329.45
BEGIN DESCRIPTION:
441s8u footbridge not being included structurally.
Set location of n = 0.99 special ineffective area based on ~ 1:1 contraction / expansion ratios from nearest bridge openings and d/s widths of 1% annual chance water surface
Bank Station offset =      2899
Block in right overbank at watershed divide. LOB block near water canal
END DESCRIPTION:
XS GIS Cut Line= 6
     3217615.508    13897996.087     3217355.638    13898903.323
     3216934.631    13899899.416     3216509.284    13900077.368
     3216218.485     13900420.25     3215656.687    13900956.734
#Sta/Elev= 30
       0   48.61  100.36   45.04  209.31   48.29  274.99    47.4  421.84    48.6
  607.63   46.82 1356.42   47.21 2031.32   46.78 2077.52   44.99 2090.72   38.06
 2095.54   37.78 2100.95   36.07 2104.73   38.36 2128.94   43.76 2158.12   45.42
 2342.58   46.71 2464.63   45.22 2520.42   46.71 2584.61   45.62 2746.11   48.17
 2999.39   47.76 3044.29   45.66 3217.59   44.88 3264.47   46.44 3517.84   45.89
 3580.37   43.37 3588.65      45 3616.55   46.36 3663.34   42.03 3715.49    49.9
#Mann= 5 ,-1 , 0
       0     .99       0 1356.42    .085       0 2095.54    .045       0
 2104.73    .085       0 2746.11     .99       0
#Block Obstruct= 2 , 0
       0  421.84      50 3616.55       0      50
Bank Sta=2095.54,2104.73
XS Rating Curve= 0
Exp/Cntr=.3,.1

Type RM Length L Ch R = 1 ,23081.95,91.17,91.04,86.65
BEGIN DESCRIPTION:
441v26
Bank Station offset =      3898
Block in right overbank at watershed divide. LOB block at roadway
END DESCRIPTION:
XS GIS Cut Line= 6
     3216678.658    13898694.435     3216545.652    13899830.294
     3216426.726    13899954.819     3216126.893    13900345.428
     3216062.652    13900411.445     3215497.251    13900830.189
#Sta/Elev= 30
       0   46.69  239.44   47.26  260.28   45.99  396.21    47.1  694.74    45.8
  716.82   46.73  751.01   45.37  769.06   46.35 1032.67   45.85 1078.04   43.78
 1096.13   37.12 1097.69   34.67 1101.95   34.12 1106.56   35.17  1125.4   43.76
 1156.12   45.19 1313.78   47.01 1452.27   45.29 1490.09   46.82 1527.91   45.42
 1679.19   48.04 1943.67   45.05 1978.48   46.19 2124.19   46.34 2349.95   45.82
 2456.11   44.11 2498.12   45.36 2534.06   42.71 2583.94   49.58 2603.97    49.7
#Mann= 5 ,-1 , 0
       0     .99       0  396.21    .085       0 1078.04    .045       0
  1125.4    .085       0 1679.19     .99       0
#Block Obstruct= 2 , 0
       0  239.44      50 2498.12       0      50
Bank Sta=1078.04,1125.4
XS Rating Curve= 0
Exp/Cntr=.3,.1

Type RM Length L Ch R = 1 ,22990.91,127.06,127.75,127.32
BEGIN DESCRIPTION:
441s7u footbridge not being included structurally
Bank Station offset =      3887
Block in right overbank at watershed divide.
END DESCRIPTION:
XS GIS Cut Line= 6
     3216558.457    13898687.098     3216465.835    13899751.593
     3216457.872     13899850.21     3216118.641    13900331.674
     3216041.425    13900403.726     3215462.516    13900791.595
#Sta/Elev= 30
       0   46.85  266.94    45.7  300.72   46.36  507.84   46.57  656.92   45.96
  703.58   44.91  718.64   46.14 1012.35   46.11 1063.14   45.69 1090.08   40.81
 1097.85   37.13 1113.29   35.32  1115.2   35.65 1124.13   42.88  1174.4   45.95
 1249.82   47.04 1348.89    46.9 1421.42   45.12  1464.5   46.76 1501.19   45.35
 1643.11   47.92 1878.35   45.09  1904.7   45.98 2082.69   46.32  2254.2   45.92
 2383.69   44.28 2445.66   45.49 2491.18   42.79 2545.23   49.75 2558.87   49.83
#Mann= 4 ,-1 , 0
       0    .095       0 1090.08    .045       0 1124.13    .095       0
 1249.82     .99       0
#Block Obstruct= 2 , 0
       0                 2445.66       0      50
Bank Sta=1090.08,1124.13
XS Rating Curve= 0
Exp/Cntr=.3,.1