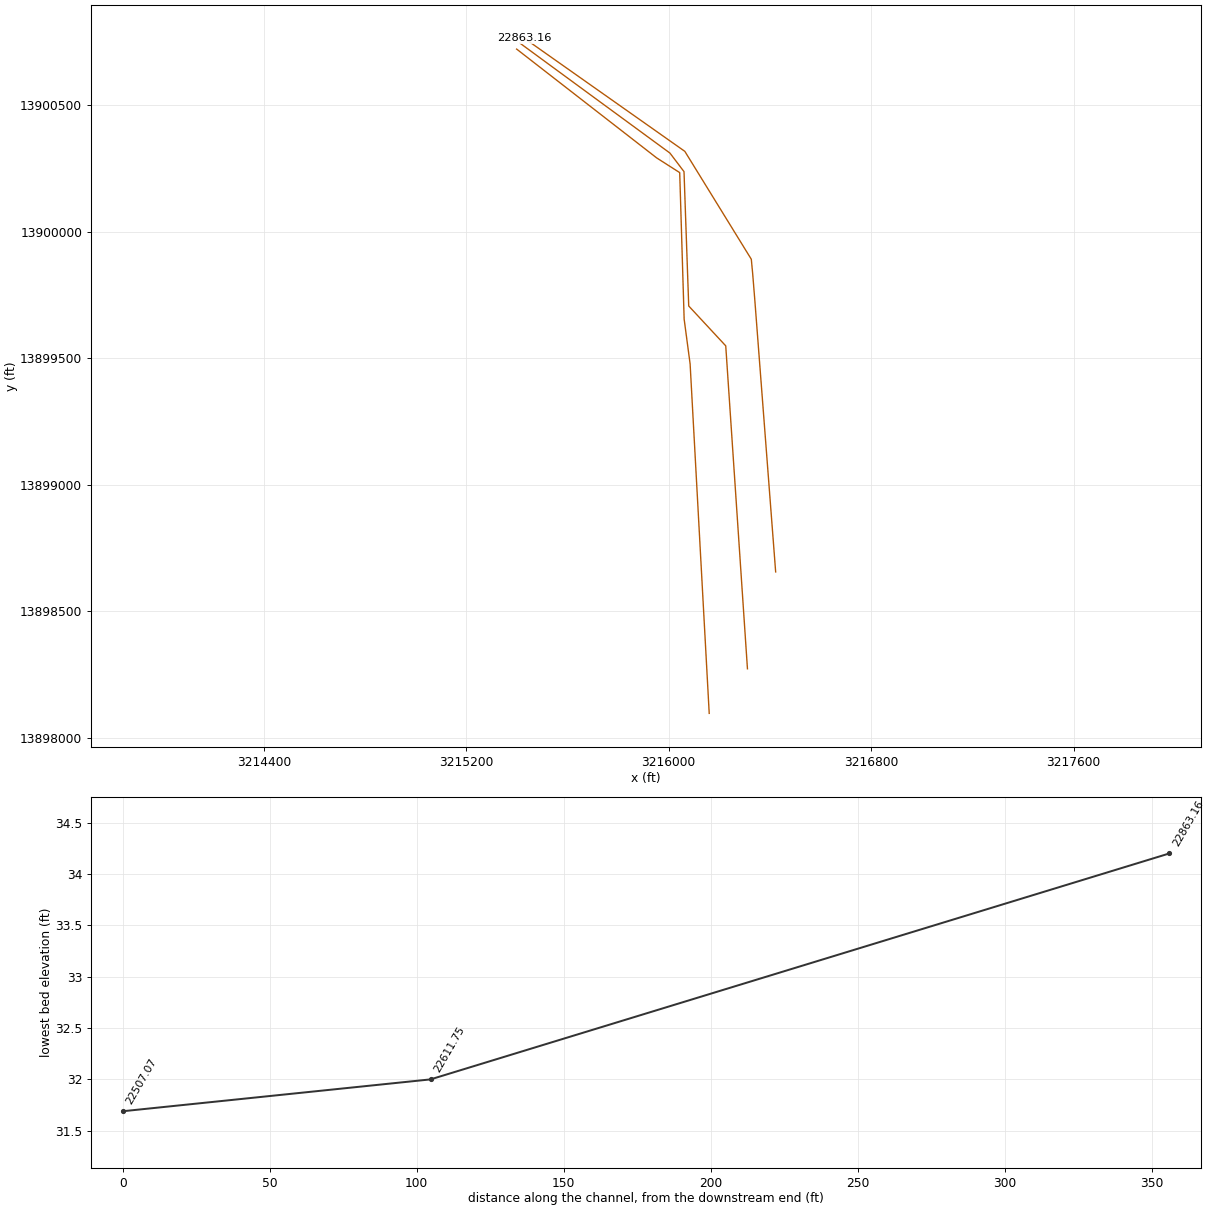
HEC-RAS study R100-00-00.prj: R100-00-00

--- R100-00-00.g01 (geometry) --- (continued)

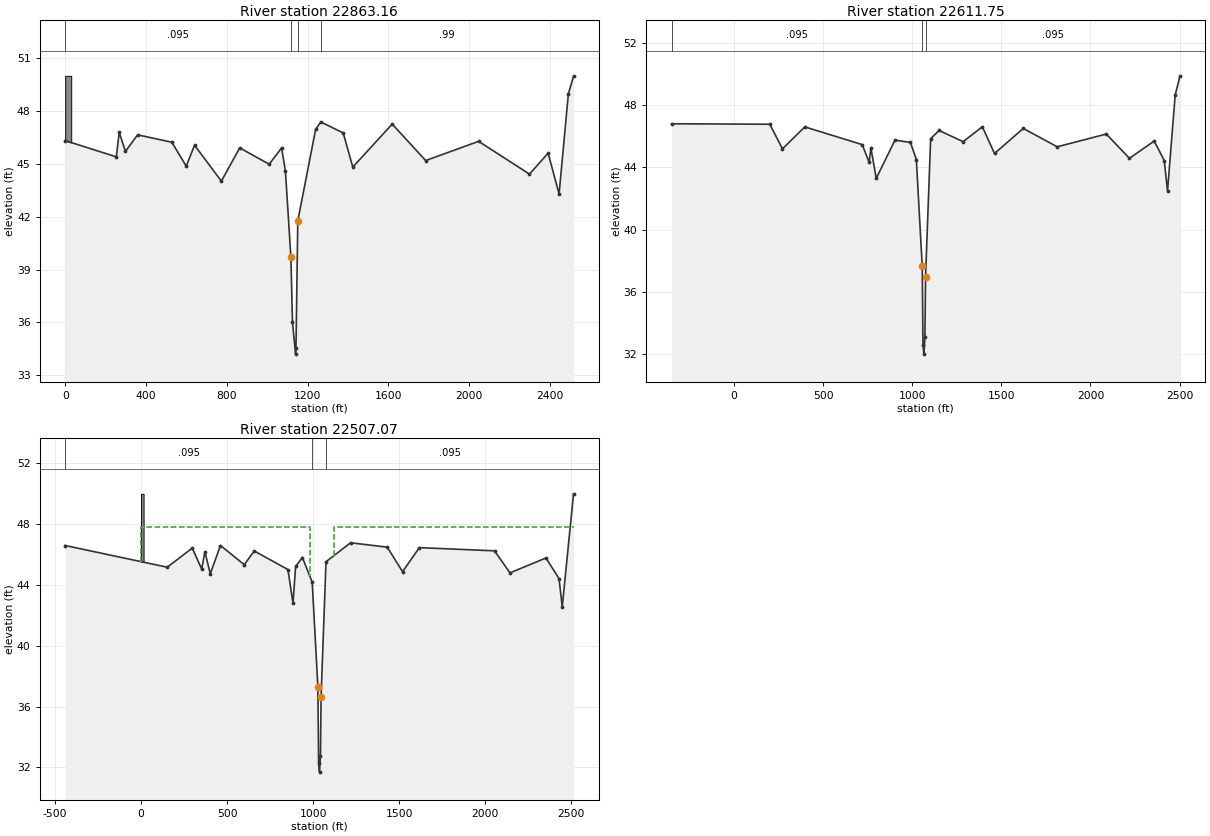
Type RM Length L Ch R = 1 ,22863.16,241.27,251.41,275.9
BEGIN DESCRIPTION:
copy of 441s7u -- d/s footbridge not being included structurally, elev adj based on slope btwn 441s7 and 441s6
Bank Station offset =      3860
Block in right overbank at watershed divide. LOB block added at private driveway.
END DESCRIPTION:
XS GIS Cut Line= 6
     3216422.595    13898655.745     3216339.832    13899734.705
       3216331.9    13899832.932     3216326.384    13899891.427
     3216063.625     13900317.92     3215429.711    13900764.579
#Sta/Elev= 30
       0   46.32  253.03    45.4  267.35   46.79  298.07   45.71  358.34   46.65
  527.87   46.23  599.04   44.87  640.22   46.06  772.96   44.02  863.58   45.91
 1009.62   44.98 1070.99   45.91 1090.09   44.57 1117.03   39.69  1124.8   36.01
 1140.24    34.2 1142.15   34.53 1151.08   41.76 1239.43   46.96 1264.81   47.38
 1375.88   46.76 1423.37   44.82 1618.35   47.26 1784.11   45.19 2046.06   46.28
 2297.89   44.42 2390.21   45.61 2444.28   43.29 2490.15   48.97 2515.84   49.97
#Mann= 4 ,-1 , 0
       0    .095       0 1117.03    .045       0 1151.08    .095       0
 1264.81     .99       0
#Block Obstruct= 2 , 0
       0   29.82      50 2391.62       0      50
Bank Sta=1117.03,1151.08
XS Rating Curve= 0
Exp/Cntr=.3,.1

Type RM Length L Ch R = 1 ,22611.75,118.76,104.68,88.54
BEGIN DESCRIPTION:
441s6u; xs 4/4 Pecan St (survey here)
Bank Station offset =      3934
Block in right overbank at watershed divide. LOB block at roadway
END DESCRIPTION:
XS GIS Cut Line= 6
 3216311.113506213898272.9066065      3216225.32    13899549.197
     3216078.979    13899706.787     3216060.378     13900237.76
     3216004.761      13900311.1     3215412.344    13900745.282
#Sta/Elev= 30
    -350    46.8  200.61   46.77  271.75   45.19  397.16    46.6  719.33   45.46
  758.19   44.32  767.89   45.25  797.92   43.29  903.04   45.75  989.57    45.6
 1023.04    44.5    1056   37.63  1060.3   32.57 1065.51      32 1070.97   33.09
 1074.69   36.97 1103.14   45.84 1150.13   46.37 1285.49   45.65 1393.28   46.61
 1461.54   44.89 1623.02    46.5  1813.3   45.32 2088.79   46.14 2218.73   44.58
 2357.54   45.69 2413.99   44.44 2432.42   42.49 2475.35   48.64 2502.38   49.88
#Mann= 3 ,-1 , 0
    -350    .095       0    1056    .045       0 1074.69    .095       0
#Block Obstruct= 2 , 0
       0     -20      50 2357.54       0      50
Bank Sta=1056,1074.69
XS Rating Curve= 0
Exp/Cntr=.5,.3

Type RM Length L Ch R = 1 ,22507.07,77.55,71.14,63.2
BEGIN DESCRIPTION:
copy of 441s6u; xs 3/4 Pecan St
channel elevations adjusted based on slope between 441s5 and 441s6
Bank Station offset =      3963
Block in right overbank at watershed divide. LOB block at roadway
END DESCRIPTION:
XS GIS Cut Line= 6
 3216159.985347213898096.6890756     3216084.542    13899477.281
     3216060.918    13899654.678     3216043.355    13900233.913
     3215952.659    13900291.803     3215398.836    13900722.126
#Sta/Elev= 30
    -440    46.6  152.95   45.17  297.96   46.43   352.8   45.05  371.47   46.19
  402.67   44.74  461.94    46.6  600.13   45.34  658.07   46.24  853.72   45.02
  883.35    42.8  898.36   45.22  938.03   45.81   994.8   44.19 1027.76   37.32
 1032.06   32.26 1037.27   31.69 1042.73   32.78 1046.45   36.66  1074.9   45.53
 1217.81   46.78 1430.98   46.49 1519.68   44.88 1617.32   46.46 2053.86   46.25
 2143.77    44.8 2352.85   45.78 2428.64   44.42 2447.31   42.57 2512.87      50
#Mann= 3 ,-1 , 0
    -440    .095       0   994.8    .045       0  1074.9    .095       0
#XS Ineff= 2 , 0
       0     980   47.84    1120       0   47.82
Permanent Ineff=
       F       F
#Block Obstruct= 2 , 0
       0   15.37      50 2352.85       0      50
Bank Sta=1027.76,1046.45
XS Rating Curve= 0
Exp/Cntr=.5,.3