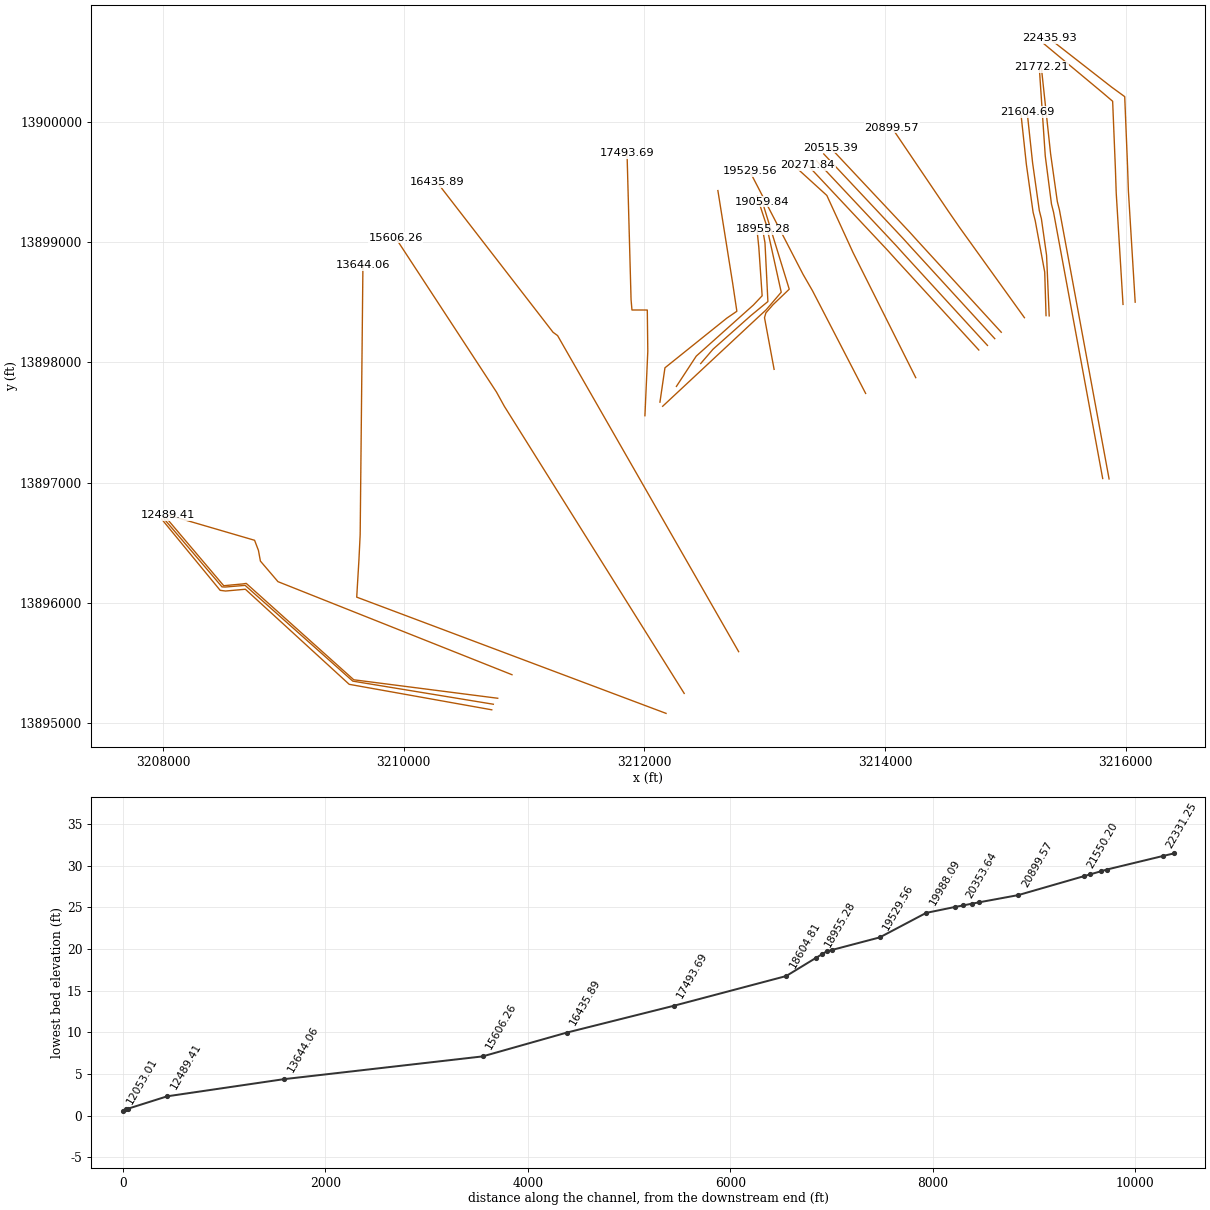
HEC-RAS study R100-00-00.prj: R100-00-00

--- R100-00-00.g01 (geometry) --- (continued)

Type RM Length L Ch R = 3 ,22471.50,,,
BEGIN DESCRIPTION:
Pecan St., 441s6, concrete bridge
added 0.7' to TR elevations for high chord based on presence of sidewalks along the road on both sides as per survey notes; road ends around station 1600 due to fact that section 3 crosses road.
Blocks included in sections at wshed divide; road ends where the section tails off in another direction
END DESCRIPTION:
Bridge Culvert--1,0,-1,-1, 0
Deck Dist Width WeirC Skew NumUp NumDn MinLoCord MaxHiCord MaxSubmerge Is_Ogee
15.57,40,2.6,0, 14, 14, , , .95, 0, 0,0,,
     .84  940.54  952.04  976.44  992.09 1036.84 1090.42 1106.64 1130.51 1138.84
 1155.84    1300    1450    1600
   47.87   47.87   47.84   47.95   47.97   47.94   47.95   47.93   47.99   47.96
   47.82   46.64   46.11   46.14
                                   44.42   44.39    44.4   44.38
                                
   14.84  940.54  952.04  976.44  992.09 1036.84 1090.42 1106.64 1130.51 1138.84
 1155.84 1315.59 1465.59 1615.59
   47.87   47.87   47.84   47.95   47.97   47.94   47.95   47.93   47.99   47.96
   47.82   46.64   46.11   46.14
                                   44.42   44.39    44.4   44.38
                                
Pier Skew, UpSta & Num, DnSta & Num=  ,1023.11, 4 ,1023.11, 4 , 3 , 3 , 0 ,0,
     1.3     1.3     2.5     2.5
   36.33   42.62   42.62   45.12
     1.3     1.3    2.25    2.25
   36.33   42.62   42.62   45.12
Pier Skew, UpSta & Num, DnSta & Num=  ,1051.68, 4 ,1051.68, 4 , 3 , 3 , 0 ,0,
     1.3     1.3     2.5     2.5
   36.92    42.6    42.6    45.1
     1.3     1.3    2.25    2.25
   36.92    42.6    42.6    45.1
BR Coef=-1 , 1 , 1 ,1.25, 0 ,,,.8,-1,2,0,
WSPro=,,,, 1 ,,,, 0 ,,,, 0 ,,,,-1 ,-1 ,-1 , 0 , 0 , 0 , 0 , 0
BC Design=,, 0 ,, 0 ,,,,,,
BC HTab HWMax=50

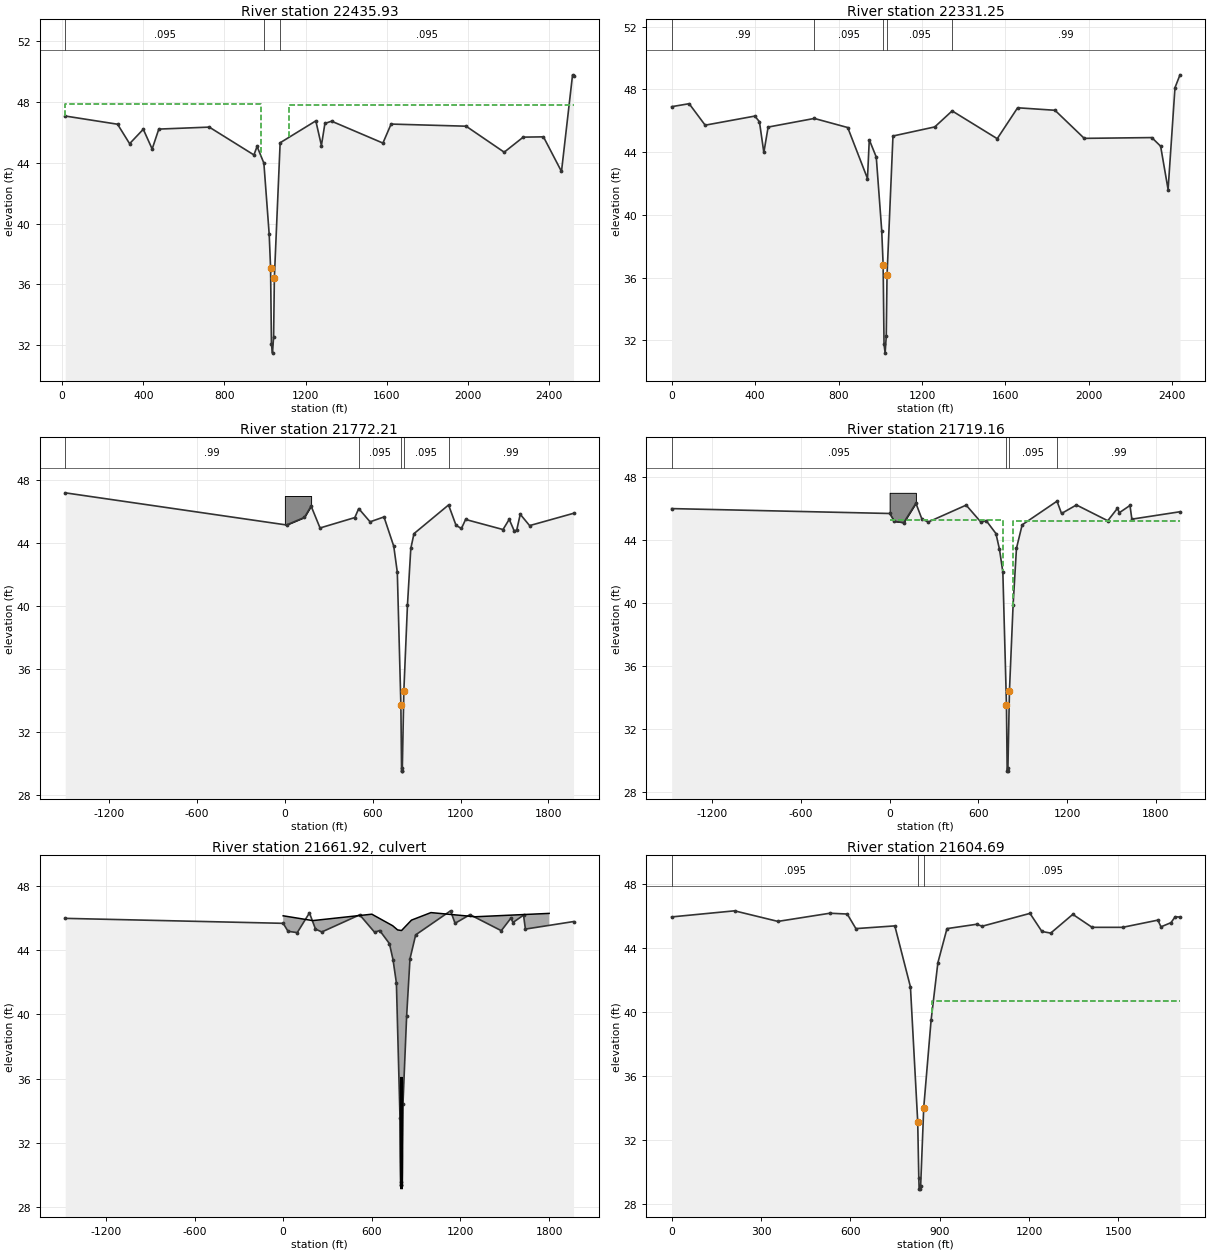
Type RM Length L Ch R = 1 ,22435.93,102.47,104.68,106.82
BEGIN DESCRIPTION:
copy of 441s6u; xs 2/4 Pecan St
channel elevations adjusted based on slope between 441s5 and 441s6
Bank Station offset =      3979
 Block in right overbank at watershed divide.
END DESCRIPTION:
XS GIS Cut Line= 6
     3216079.229    13898500.689     3216022.721    13899426.566
     3216016.084    13899622.703     3215992.186    13900208.628
      3215883.19    13900287.944     3215364.102     13900693.18
#Sta/Elev= 30
   15.59   47.08  273.45   46.54  332.84   45.26  400.11   46.21  443.86   44.91
  476.55   46.22  725.15   46.35  945.08   44.52  960.61   45.08  994.08   43.98
 1020.29   39.29 1027.04   37.11 1031.34   32.05 1036.55   31.48 1042.01   32.57
 1045.73   36.45 1074.18   45.32 1249.86   46.76 1277.47   45.14 1294.71   46.59
 1327.52   46.74 1580.38    45.3 1620.63   46.55 1990.07   46.41 2177.68    44.7
 2271.46   45.69 2371.05   45.71 2459.88   43.43 2514.41   49.79 2519.19   49.72
#Mann= 3 ,-1 , 0
   15.59    .095       0  994.08    .045       0 1074.18    .095       0
#XS Ineff= 2 , 0
       0     980   47.84    1120       0   47.82
Permanent Ineff=
       F       F
#Block Obstruct= 2 , 0
       0                 2322.15       0      50
Bank Sta=1027.04,1045.73
XS Rating Curve= 0
Exp/Cntr=.5,.3

Type RM Length L Ch R = 1 ,22331.25,549.75,559.03,563.09
BEGIN DESCRIPTION:
copy of 441s6u; xs 1/4 Pecan St
channel elevations adjusted based on slope between 441s5 and 441s6
Bank Station offset =      3977
Block in right overbank at watershed divide.
END DESCRIPTION:
XS GIS Cut Line= 6
     3215978.127    13898482.083      3215921.62     13899407.96
     3215914.982    13899604.097     3215891.893    13900170.194
     3215806.002    13900243.561     3215319.719    13900648.797
#Sta/Elev= 30
       0   46.89   83.77   47.08  160.51   45.71  398.55   46.29  420.66   45.93
  441.77   43.97  462.29   45.59  683.66   46.14   843.8   45.56  938.49   42.31
   947.1   44.78  980.57   43.68 1006.78   38.99 1013.53   36.81 1017.83   31.75
 1023.04   31.18  1028.5   32.27 1032.22   36.15 1060.67   45.02 1261.06    45.6
 1344.22   46.62 1560.36   44.85 1658.11   46.82 1837.17   46.66 1977.46   44.87
 2301.22   44.92 2343.54   44.37 2379.32   41.61 2412.29    48.1 2436.38   48.92
#Mann= 5 ,-1 , 0
       0     .99       0  683.66    .095       0 1013.53    .045       0
 1032.22    .095       0 1344.22     .99       0
#Block Obstruct= 2 , 0
       0                 2301.22       0      50
Bank Sta=1013.53,1032.22
XS Rating Curve= 0
Exp/Cntr=.3,.1

Type RM Length L Ch R = 1 ,21772.21,53.67,53.05,53
BEGIN DESCRIPTION:
441s5u; xs 4/4 Miller Wilson Rd (survey here)
Bank Station offset =      4201
LOB block at roadway, ROB block at roadway
END DESCRIPTION:
XS GIS Cut Line= 6
 3215862.306888113897031.8275624     3215590.057    13898506.914
     3215449.461    13899268.682     3215432.212    13899336.542
     3215376.136    13899735.061 3215299.016270613900454.8468486
#Sta/Elev= 30
   -1500    47.2    11.3   45.16  133.31   45.64  179.09   46.36   240.1   44.97
   477.6   45.63  504.09    46.2  581.72   45.36  676.72   45.67  743.47   43.81
  767.68   42.16  792.06   33.76  796.83   29.56  799.16   29.54  801.97   29.73
  812.32   34.63  837.03   40.08  859.82   43.67   881.5   44.61 1117.72   46.43
 1168.99   45.13 1205.71   44.94 1233.92   45.51 1489.39   44.87 1531.81   45.52
 1566.16   44.78 1583.25   44.84 1607.12   45.84 1671.02   45.12    1971    45.9
#Mann= 5 ,-1 , 0
   -1500     .99       0  504.09    .095       0  792.06    .045       0
  812.32    .095       0 1117.72     .99       0
#Block Obstruct= 2 , 0
       0  179.09      47 1607.12       0      47
Bank Sta=792.06,812.32
XS Rating Curve= 0
Exp/Cntr=.5,.3

Type RM Length L Ch R = 1 ,21719.16,113.44,114.48,113.36
BEGIN DESCRIPTION:
copy of 441s5u; xs 3/4 Miller Wilson Rd
channel elevations adjusted based on slope between 441v25 and 441s5
Bank Station offset =      4202
section extended left and right to watershed divide
LOB block at roadway, ROB block at roadway
END DESCRIPTION:
XS GIS Cut Line= 6
 3215809.231548613897035.2219965     3215400.926    13899247.492
     3215383.676    13899315.352     3215331.924    13899715.873
     3215303.595    13900134.272 3215283.522173313900430.7332452
#Sta/Elev= 30
   -1475      46       0   45.69   32.85   45.19   95.48   45.11  177.74   46.34
  218.73   45.33  261.65   45.15  517.86   46.22  618.89   45.13  653.24   45.24
  719.25   44.42  743.38   43.42  766.19   41.97  790.57   33.57  795.34   29.37
  797.67   29.35  800.48   29.54  810.83   34.44  835.54   39.89  858.33   43.48
  896.87   44.97 1132.69   46.47 1163.25   45.69  1264.1   46.23 1476.18   45.23
 1541.83   46.02 1554.73   45.74 1626.52    46.2 1639.21   45.33    1965    45.8
#Mann= 4 ,-1 , 0
   -1475    .095       0  790.57    .045       0  810.83    .095       0
 1132.69     .99       0
#XS Ineff= 2 , 0
       0     765   45.28     835       0   45.24
Permanent Ineff=
       F       F
#Block Obstruct= 2 , 0
       0  177.74      47 1626.52       0      47
Bank Sta=790.57,810.83
XS Rating Curve= 0
Exp/Cntr=.5,.3

Type RM Length L Ch R = 2 ,21661.92,,,
BEGIN DESCRIPTION:
Miller Wilson Rd., 441s5, metal culvert
Assumed 2 ft between culverts, not given in survey notes
Ineffective flow stations widened at this structure due to initial checkRAS note that the velocity head difference is >0
Road values beyond survey points determined from TIN generated from LIDAR.
END DESCRIPTION:
Bridge Culvert--1,0,-1,-1, 0
Deck Dist Width WeirC Skew NumUp NumDn MinLoCord MaxHiCord MaxSubmerge Is_Ogee
47,21,2.6,0, 10, 10, , , .95, 0, 0,0,,
       0     200     600   741.1  774.15     801  868.23    1000    1300    1800
   46.16   45.86   46.26   45.54   45.28   45.24   45.89   46.36    46.1   46.31
                                                                                
       0     235     635   776.1  809.15     836  903.23    1035    1335    1835
   46.16   45.86   46.26   45.54   45.28   45.24   45.89   46.36    46.1   46.31
                                                                                
BR Coef=-1 , 0 , 0 ,, 0 ,,,.8,0,,0,
WSPro=,,,, 1 ,,,, 0 ,,,, 0 ,,,,-1 ,-1 ,-1 , 0 , 0 , 0 , 0 , 0
Multiple Barrel Culv=1,7,,98.8,.015,.5,1,55,1,29.1,29.1, 2,441s5       , 0 ,7.84
   796.5   831.5   805.5   840.5
Culvert Bottom n=.015
BC Design=,, 0 ,, 0 ,,,,,,
BC HTab HWMax=46.47

Type RM Length L Ch R = 1 ,21604.69,54.69,54.49,54.18
BEGIN DESCRIPTION:
copy of 441s5u; xs 2/4 Miller Wilson Rd
channel elevations adjusted based on slope between 441v25 and 441s5
Bank Station offset =      4167
END DESCRIPTION:
XS GIS Cut Line= 6
     3215364.612    13898386.586      3215342.82    13898889.972
     3215299.807    13899193.688     3215282.557    13899261.548
     3215226.481    13899660.068     3215181.319    13900081.581
#Sta/Elev= 30
       0   45.94  211.11   46.32  356.78   45.66  531.17   46.17  589.53   46.12
  618.62   45.21  749.34   45.38   801.8   41.57  826.18   33.17  829.87   29.65
  830.95   28.97  833.28   28.95  836.09   29.14  846.44   34.04  871.15   39.49
  893.94   43.08   924.5   45.21 1023.76   45.48 1042.86   45.36  1203.2   46.16
 1243.36   45.03 1272.84   44.93 1347.01    46.1 1411.82   45.29 1514.25   45.29
  1632.8   45.74 1643.08   45.32 1676.58   45.58 1690.89   45.95 1706.99   45.93
#Mann= 3 ,-1 , 0
       0    .095       0  826.18    .045       0  846.44    .095       0
#XS Ineff= 2 , 0
       0     804    40.7     874       0    40.7
Permanent Ineff=
       F       F
Bank Sta=826.18,846.44
XS Rating Curve= 0
Exp/Cntr=.5,.3

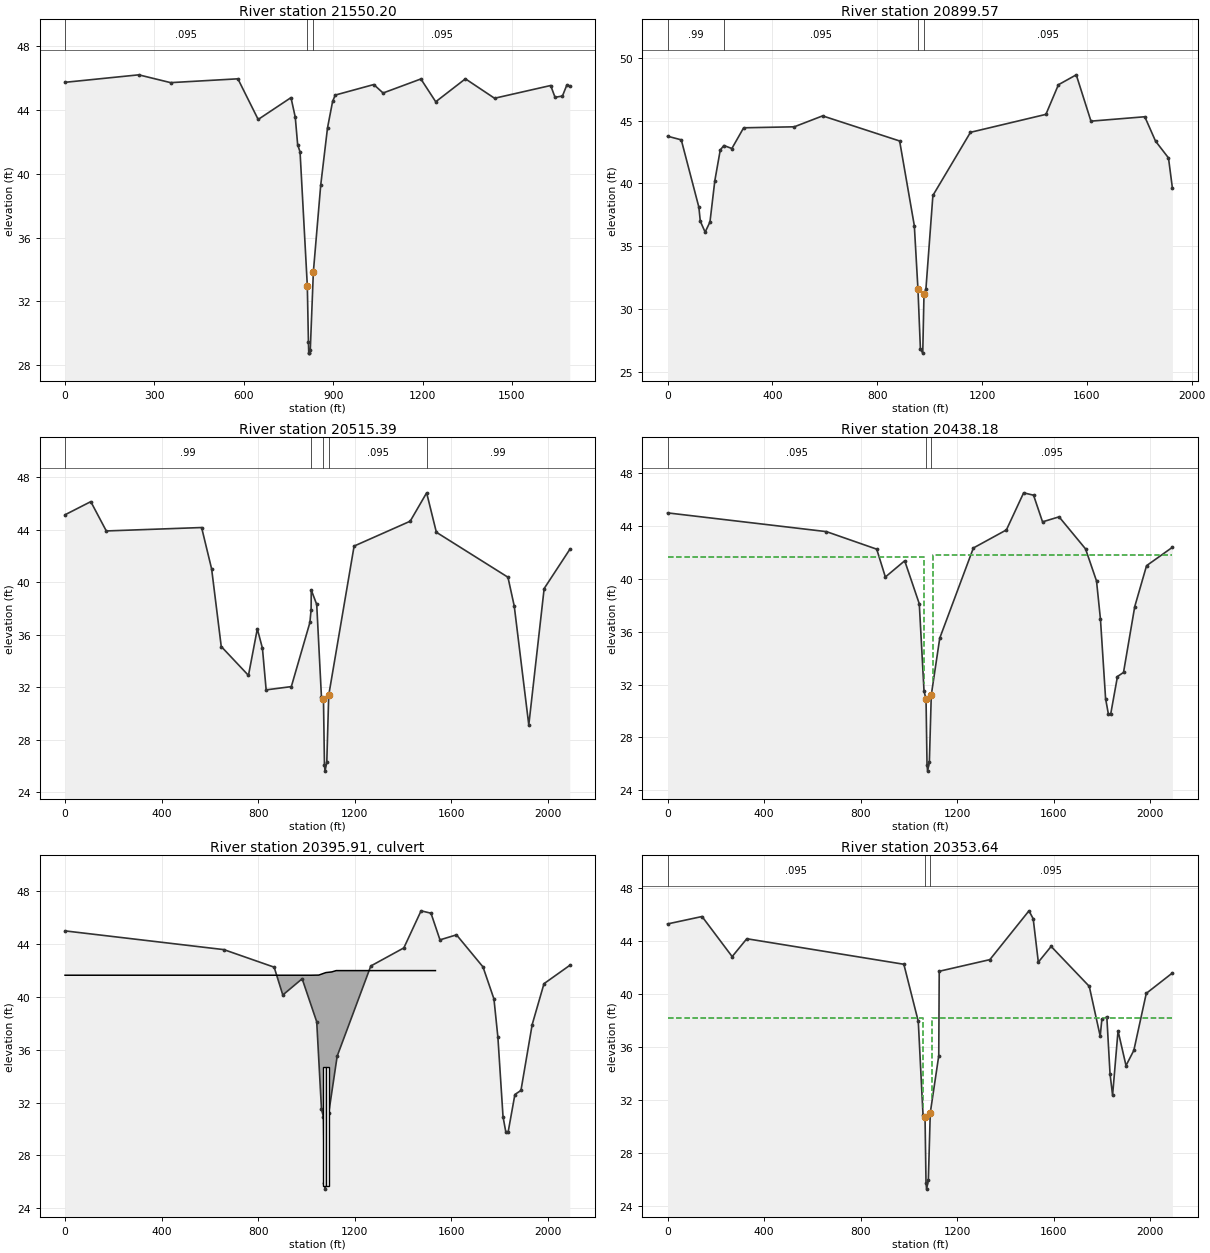
Type RM Length L Ch R = 1 ,21550.20,645.77,650.63,659.41
BEGIN DESCRIPTION:
copy of 441s5u; xs 1/4 Miller Wilson Rd
channel elevations adjusted based on slope between 441v25 and 441s5
Bank Station offset =      4180
END DESCRIPTION:
XS GIS Cut Line= 6
     3215338.462    13898388.765     3215327.442     13898750.08
     3215248.193    13899179.462     3215230.943    13899247.322
     3215174.867    13899645.841     3215129.705    13900067.354
#Sta/Elev= 30
       0   45.75  247.45   46.22  354.43   45.73  580.26   45.97  648.37   43.42
  758.53   44.79   772.9   43.56  780.89   41.84  788.98   41.38  813.36   32.98
  817.05   29.46  818.13   28.78  820.46   28.76  823.27   28.95  833.62   33.85
  858.33    39.3  881.12   42.89  898.22   44.55  907.09   44.95 1036.45   45.61
 1067.68   45.08 1194.55   45.96  1244.4   44.53 1344.02   45.97 1441.87   44.75
 1630.29   45.55  1644.9   44.81 1669.78   44.89 1684.12   45.56 1694.51   45.53
#Mann= 3 ,-1 , 0
       0    .095       0  813.36    .045       0  833.62    .095       0
Bank Sta=813.36,833.62
XS Rating Curve= 0
Exp/Cntr=.3,.1

Type RM Length L Ch R = 1 ,20899.57,381.68,384.18,387.43
BEGIN DESCRIPTION:
441v25
Bank Station offset =      4026
Block added to right overbank
END DESCRIPTION:
XS GIS Cut Line= 4
     3215158.862     13898371.73     3214619.623    13899121.745
     3214525.961    13899257.421     3214056.843    13899951.291
#Sta/Elev= 30
       0   43.76   52.18   43.47   119.4    38.1  124.77   36.99  143.24   36.12
  161.71   36.93  180.19   40.21  200.94   42.66   214.7   43.02  245.25   42.78
   290.2   44.43  483.49   44.51  591.51   45.38  885.43   43.38  941.51   36.63
  955.39   31.55  964.73    26.8  973.63   26.48  978.37   31.17  985.79    31.6
 1012.35   39.04 1155.74   44.07  1443.6    45.5 1491.33   47.86  1559.4   48.65
 1615.54   44.96 1820.94   45.31  1861.9   43.37 1911.32   42.03 1926.18   39.65
#Mann= 4 ,-1 , 0
       0     .99       0   214.7    .095       0  955.39    .045       0
  978.37    .095       0
#Block Obstruct= 2 , 0
       0                  1559.4       0   48.65
Bank Sta=955.39,978.37
XS Rating Curve= 0
Exp/Cntr=.3,.1

Type RM Length L Ch R = 1 ,20515.39,76.35,77.21,76.09
BEGIN DESCRIPTION:
441s4u; xs 4/4 N Main St aka 441v24 (survey location)
Bank Station offset =      3923
END DESCRIPTION:
XS GIS Cut Line= 4
     3214966.284    13898250.628     3214271.911    13899008.825
     3214206.515    13899081.207      3213545.28    13899785.727
#Sta/Elev= 30
       0   45.12  106.75   46.12  171.02   43.89     566   44.15  607.54      41
  647.36    35.1  760.18    32.9  796.84   36.44  818.07   34.97  833.47    31.8
  937.85   32.05 1014.84   36.93 1019.79   37.91 1020.39    39.4 1043.04    38.3
 1062.72   31.23 1071.04   31.08 1075.09    26.1  1077.5   25.62  1084.8   26.31
 1092.78   31.39 1197.97   42.74 1430.31   44.63 1498.57   46.79 1538.88   43.79
 1835.53   40.37  1861.6   38.18 1921.89   29.13 1985.56   39.51 2091.88   42.49
#Mann= 5 ,-1 , 0
       0     .99       0 1020.39    .095       0 1071.04    .045       0
 1092.78    .095       0 1498.57     .99       0
Bank Sta=1071.04,1092.78
XS Rating Curve= 0
Exp/Cntr=.5,.3

Type RM Length L Ch R = 1 ,20438.18,83.08,84.54,83.3
BEGIN DESCRIPTION:
copy of 441s4u; xs 3/4 N Main St aka 441v24
- channel elevations adjusted based on slope between 441v23 and 441v25
Bank Station offset =      3923
END DESCRIPTION:
XS GIS Cut Line= 4
     3214912.161    13898197.417     3214217.789    13898955.614
     3214152.392    13899027.995     3213491.157    13899732.516
#Sta/Elev= 30
       0   45.01  658.18   43.59  866.64   42.26  902.47   40.15  982.61   41.38
 1043.04   38.12 1062.72    31.5 1071.04    30.9 1075.09   25.92  1077.5   25.44
  1084.8   26.13 1092.78   31.21 1127.89   35.52 1267.22   42.35 1404.08   43.72
 1475.49   46.53 1516.58   46.35 1553.83   44.33 1622.29   44.71 1732.08   42.28
 1777.52   39.85  1793.9   36.94 1815.12   30.93 1826.36    29.8 1836.35   29.77
  1864.3   32.61 1889.41   32.92 1935.95   37.91 1984.91   41.01 2091.88    42.4
#Mann= 3 , 0 , 0
       0    .095       0 1071.04    .045       0 1092.78    .095       0
#XS Ineff= 2 , 0
       0    1061   41.65    1101       0   41.85
Permanent Ineff=
       F       F
Bank Sta=1071.04,1092.78
XS Rating Curve= 0
Exp/Cntr=.5,.3

Type RM Length L Ch R = 2 ,20395.91,,,
BEGIN DESCRIPTION:
N. Main St., 441s4, concrete box culvert
Assumed dividing wall is 1 ft wide (not given in survey notes)
END DESCRIPTION:
Bridge Culvert--1,0,-1,-1, 0
Deck Dist Width WeirC Skew NumUp NumDn MinLoCord MaxHiCord MaxSubmerge Is_Ogee
22,40,2.6,0, 8, 8, , , .95, 0, 0,0,,
       0  1019.8 1051.34    1081 1105.24 1123.71    1177    1535
   41.65   41.65   41.66   41.85    41.9      42      42      42
       0       0       0       0       0       0       0       0
       0  1015.8 1047.34    1077 1101.24 1119.71    1173    1535
   41.65   41.65   41.66   41.85    41.9      42      42      42
       0       0       0       0       0       0       0       0
Multiple Barrel Culv=2,9,10,68.3,.012,.4,1,8,1,25.7,25.7, 2,441s4       , 0 ,8.12
  1075.9  1071.9  1086.9  1082.9
Culvert Bottom n=.012
BC Design=,, 0 ,, 0 ,,,,,,
BC HTab HWMax=46.53

Type RM Length L Ch R = 1 ,20353.64,81.03,81.8,81.54
BEGIN DESCRIPTION:
copy of 441s4u; xs 2/4 N Main St aka 441v24
- channel elevations adjusted based on slope between 441v23 and 441v25
Bank Station offset =      3927
END DESCRIPTION:
XS GIS Cut Line= 4
     3214851.683    13898140.978      3214157.31    13898899.175
     3214091.914    13898971.557     3213430.678    13899676.077
#Sta/Elev= 30
       0   45.29  142.74   45.85  267.54   42.82  328.22   44.17  979.09   42.24
 1038.86   37.92 1058.54   30.85 1066.86    30.7 1070.91   25.72 1073.32   25.24
 1080.62   25.93  1088.6   31.01 1123.71   35.32 1125.66   41.71 1335.55   42.59
 1497.55   46.28 1515.13   45.68 1536.36    42.4 1589.42   43.59 1747.49   40.57
 1792.82    36.8  1799.7   38.09 1820.27   38.25 1833.49   33.97  1844.1   32.33
 1866.69   37.21 1899.72   34.58 1932.18   35.73 1983.71   40.04 2091.88   41.58
#Mann= 3 , 0 , 0
       0    .095       0 1066.86    .045       0  1088.6    .095       0
#XS Ineff= 2 , 0
       0    1057    38.2    1097       0    38.2
Permanent Ineff=
       F       F
Bank Sta=1066.86,1088.6
XS Rating Curve= 0
Exp/Cntr=.5,.3

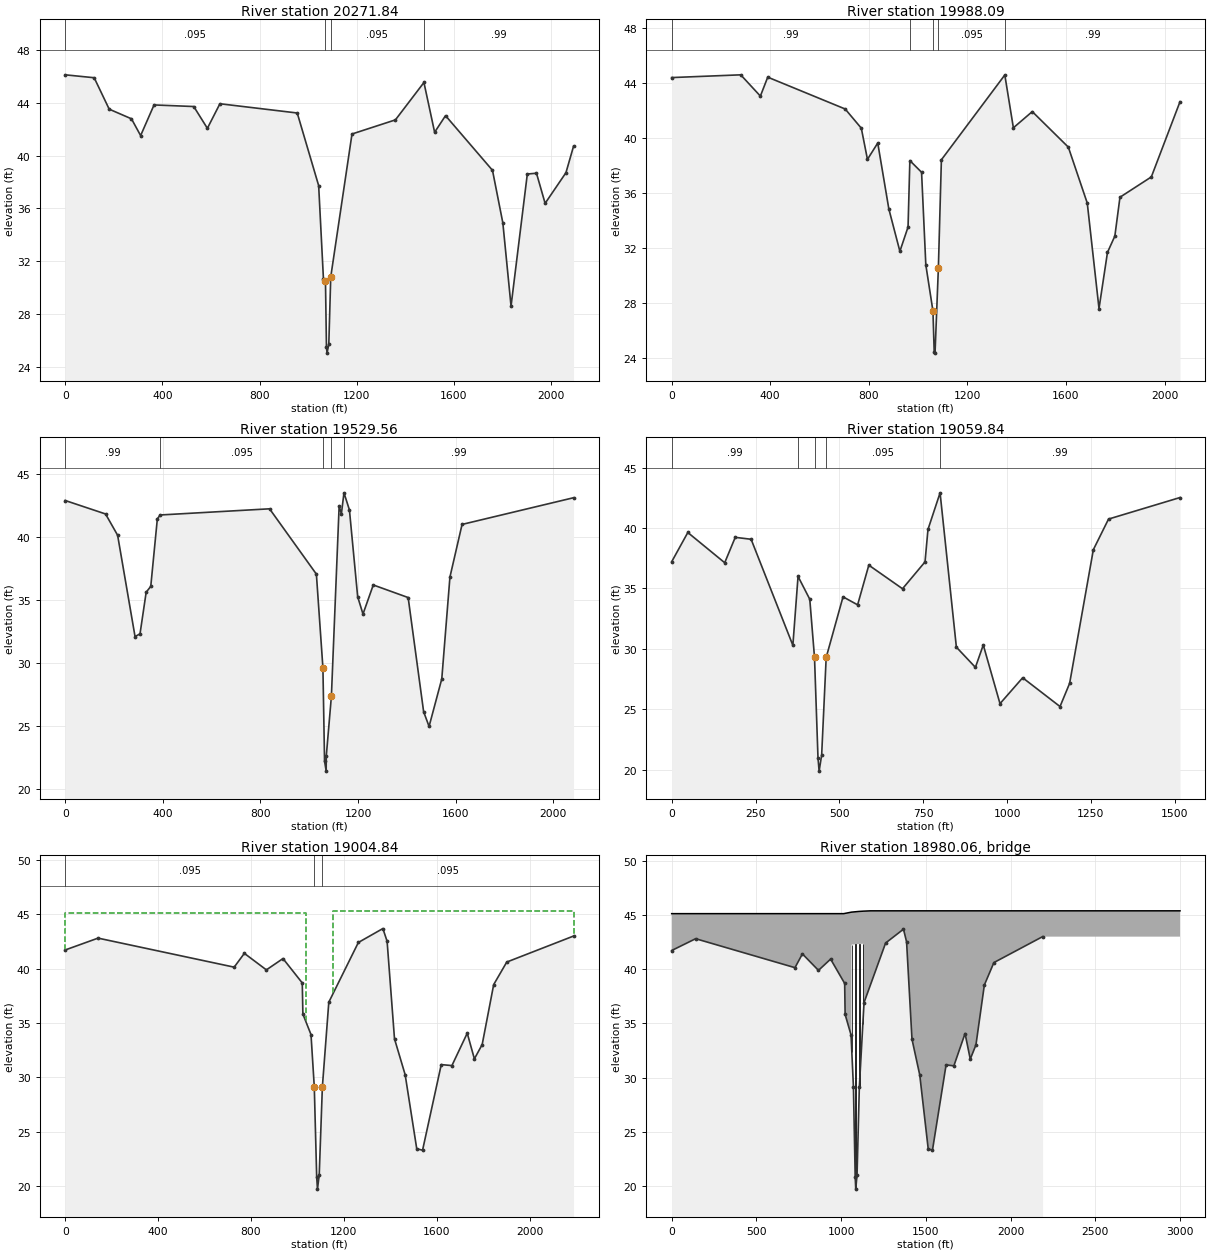
Type RM Length L Ch R = 1 ,20271.84,286.46,283.75,279.01
BEGIN DESCRIPTION:
copy of 441s4u; xs 1/4 N Main St aka 441v24
- channel elevations adjusted based on slope between 441v23 and 441v25
Bank Station offset =      3923
END DESCRIPTION:
XS GIS Cut Line= 4
     3214779.534    13898103.203     3214085.161    13898861.401
     3214019.765    13898933.782      3213358.53    13899638.303
#Sta/Elev= 30
       0   46.12   119.2    45.9  181.05   43.52  272.67   42.79  310.38   41.52
  365.57   43.84  529.02   43.72  585.06   42.07  636.64   43.93  954.84   43.23
 1043.04   37.73 1062.72   30.66 1071.04   30.51 1075.09   25.53  1077.5   25.05
  1084.8   25.74 1092.78   30.82  1180.2   41.64 1358.92   42.71 1476.24   45.54
 1520.27   41.77  1565.1   43.03 1758.37   38.89 1800.98   34.91 1834.72   28.61
 1901.71   38.61 1939.41   38.67 1974.94   36.39 2060.68   38.71 2091.88   40.71
#Mann= 4 ,-1 , 0
       0    .095       0 1071.04    .045       0 1092.78    .095       0
 1476.24     .99       0
Bank Sta=1071.04,1092.78
XS Rating Curve= 0
Exp/Cntr=.3,.1

Type RM Length L Ch R = 1 ,19988.09,462.65,458.53,458.4
BEGIN DESCRIPTION:
441v23
Bank Station offset =      3931
END DESCRIPTION:
XS GIS Cut Line= 6
     3214255.586    13897873.354      3213821.22    13898739.815
     3213736.882    13898908.272     3213732.566    13898917.238
     3213516.731    13899387.544     3213237.405    13899641.889
#Sta/Elev= 30
       0   44.42  280.18   44.62  359.97   43.07   389.8   44.45  704.08   42.13
  769.59   40.73  794.48   38.46  836.29   39.65  881.35   34.84  926.09   31.76
  959.23   33.53  966.58   38.37  1014.1   37.52 1031.36   30.77 1060.29   27.41
  1065.3   24.44 1068.76   24.34 1082.28   30.54 1094.55   38.43  1351.9   44.61
 1386.66   40.76 1463.38   41.94 1609.69   39.35 1686.54   35.27 1734.14   27.59
 1768.52   31.68 1798.47   32.87  1819.2    35.7  1946.5   37.18 2062.83   42.66
#Mann= 5 ,-1 , 0
       0     .99       0  966.58    .095       0 1060.29    .045       0
 1082.28    .095       0  1351.9     .99       0
Bank Sta=1060.29,1082.28
XS Rating Curve= 0
Exp/Cntr=.3,.1

Type RM Length L Ch R = 1 ,19529.56,481.77,469.72,441.28
BEGIN DESCRIPTION:
441v22
Bank Station offset =      3931
END DESCRIPTION:
XS GIS Cut Line= 4
      3213839.17    13897742.329     3213397.529     13898595.75
     3213318.936    13898732.023     3212876.036    13899588.539
#Sta/Elev= 30
       0    42.9  165.31   41.83  214.72   40.14  286.11   32.09  306.52   32.31
  331.67   35.61  350.52   36.08  377.39   41.43  388.76   41.75  837.19   42.24
 1029.03   37.05 1055.82   29.59 1062.43   22.21 1069.13    21.4 1069.45   22.57
 1090.48   27.34 1122.23   42.46 1131.44   41.84 1142.04   43.51  1164.4   42.15
 1198.18   35.25 1219.95   33.88 1262.07   36.19 1404.99   35.19 1468.36   26.12
 1490.67   24.95 1542.75   28.73 1576.15   36.82 1625.85      41 2082.49   43.12
#Mann= 5 ,-1 , 0
       0     .99       0  388.76    .095       0 1055.82    .045       0
 1090.48    .095       0 1142.04     .99       0
Bank Sta=1055.82,1090.48
XS Rating Curve= 0
Exp/Cntr=.3,.1

Type RM Length L Ch R = 1 ,19059.84,75.99,55.01,48.89
BEGIN DESCRIPTION:
copy of 441s3u;  xs 4/4 SPTC Railroad
Right bank station interpolated as 13.5' beyond last survey point at elevation 29.30
Channel elevations adjusted based on slope between 441s3 and 441v22
Bank Station offset =      4562
END DESCRIPTION:
XS GIS Cut Line= 6
     3213078.562    13897942.572      3212998.81    13898371.695
     3213009.962    13898411.339     3213069.987    13898479.938
     3213204.329    13898608.563     3212980.638     13899335.18
#Sta/Elev= 30
       0   37.21   48.13   39.63  158.15   37.13  189.57   39.23  236.89   39.07
  361.39    30.3  376.82      36   411.8   34.11  425.93    29.3  436.28   21.02
  439.66    19.9  447.24   21.23  460.74    29.3  510.96   34.31  554.45   33.65
  587.86   36.93  688.33   34.98  755.48    37.2  764.25   39.88  800.35   42.91
  848.95   30.15  905.71   28.48  929.18   30.33  979.03   25.48 1046.66   27.62
 1158.02   25.24 1186.68   27.16 1257.41   38.21 1302.65   40.74 1515.77   42.52
#Mann= 5 ,-1 , 0
       0     .99       0  376.82    .095       0  425.93    .045       0
  460.74    .095       0  800.35     .99       0
Bank Sta=425.93,460.74
XS Rating Curve= 0
Exp/Cntr=.5,.3

Type RM Length L Ch R = 1 ,19004.84,56.37,49.55,49.4
BEGIN DESCRIPTION:
441s3u;  xs 3/4 SPTC Railroad (SURVEY HERE)
Right bank station interpolated as 13.5' beyond last survey point at elevation 29.12
Bank Station offset =      3915
END DESCRIPTION:
XS GIS Cut Line= 6
     3212152.441     13897635.55     3212945.137     13898375.01
      3213010.97    13898435.364       3213137.7    13898583.214
     3213014.874    13899140.276     3212937.235    13899378.583
#Sta/Elev= 30
       0   41.71  141.45    42.8  727.68   40.13  771.52    41.4  866.33   39.88
  937.92   40.92 1020.91   38.68 1023.58   35.82 1058.56   33.93 1072.69   29.12
 1083.04   20.84 1086.42   19.72    1094   21.05  1107.5   29.12 1135.22   36.91
 1262.49    42.4 1368.09   43.68 1386.29   42.51 1418.14   33.54 1464.05   30.24
 1513.96   23.43 1539.02    23.3  1619.5   31.17 1665.42   31.08 1731.43   34.06
 1762.15    31.7  1795.7   33.01 1845.33   38.53 1901.62    40.6 2189.17   42.99
#Mann= 3 , 0 , 0
       0    .095       0 1072.69     .05       0  1107.5    .095       0
#XS Ineff= 2 , 0
       0    1038   45.11    1154       0   45.31
Permanent Ineff=
       F       F
Bank Sta=1072.69,1107.5
XS Rating Curve= 0
Exp/Cntr=.5,.3

Type RM Length L Ch R = 3 ,18980.06,,,
BEGIN DESCRIPTION:
441s3, SPTC RR crossing
Ineffective flow stations widened at this structure due to initial checkRAS note that the velocity head difference is >0
Downstream bridge shifted with cross section 475.45' to allign channels
END DESCRIPTION:
Bridge Culvert--1,0,-1,-1, 0
Deck Dist Width WeirC Skew NumUp NumDn MinLoCord MaxHiCord MaxSubmerge Is_Ogee
15.575,18.4,2.6,0, 9, 9, , , .95, 0, 0,0,,
    -.03 1014.93  1061.2 1061.21 1102.01 1130.79  1130.8  1172.9 2999.97
   45.11   45.11   45.25   45.25   45.31   45.34   45.34   45.37   45.37
       0       0       0   42.25   42.31   42.34       0       0       0
   26.97 1014.93  1061.2 1061.21 1102.01 1130.79  1130.8  1172.9 3026.97
   45.11   45.11   45.25   45.25   45.31   45.34   45.34   45.37   45.37
       0       0       0   42.25   42.31   42.34       0       0       0
Pier Skew, UpSta & Num, DnSta & Num=  ,1063.12, 4 ,1063.12, 4 , 3 , 3 , 0 ,0,
       2       2     2.5     2.5
      15   42.11   42.11      46
       2       2     2.5     2.5
      15   42.11   42.11      46
Pier Skew, UpSta & Num, DnSta & Num=  ,1084.97, 4 ,1084.97, 4 , 3 , 3 , 0 ,0,
       2       2     2.5     2.5
      15   42.11   42.11      46
       2       2     2.5     2.5
      15   42.11   42.11      46
Pier Skew, UpSta & Num, DnSta & Num=  ,1107.4, 4 ,1107.4, 4 , 3 , 3 , 0 ,0,
       2       2     2.5     2.5
      15   42.11   42.11      46
       2       2     2.5     2.5
      15   42.11   42.11      46
Pier Skew, UpSta & Num, DnSta & Num=  ,1128.17, 4 ,1128.17, 4 , 3 , 3 , 0 ,0,
       2       2     2.5     2.5
      15   42.11   42.11      46
       2       2     2.5     2.5
      15   42.11   42.11      46
BR Coef=-1 , 1 , 1 ,.9, 0 ,,,.8,-1,1.2,0,
WSPro=,,,, 1 ,,,, 0 ,,,, 0 ,,,,-1 ,-1 ,-1 , 0 , 0 , 0 , 0 , 0
BC Design=,, 0 ,, 0 ,,,,,,
BC HTab HWMax=43.68

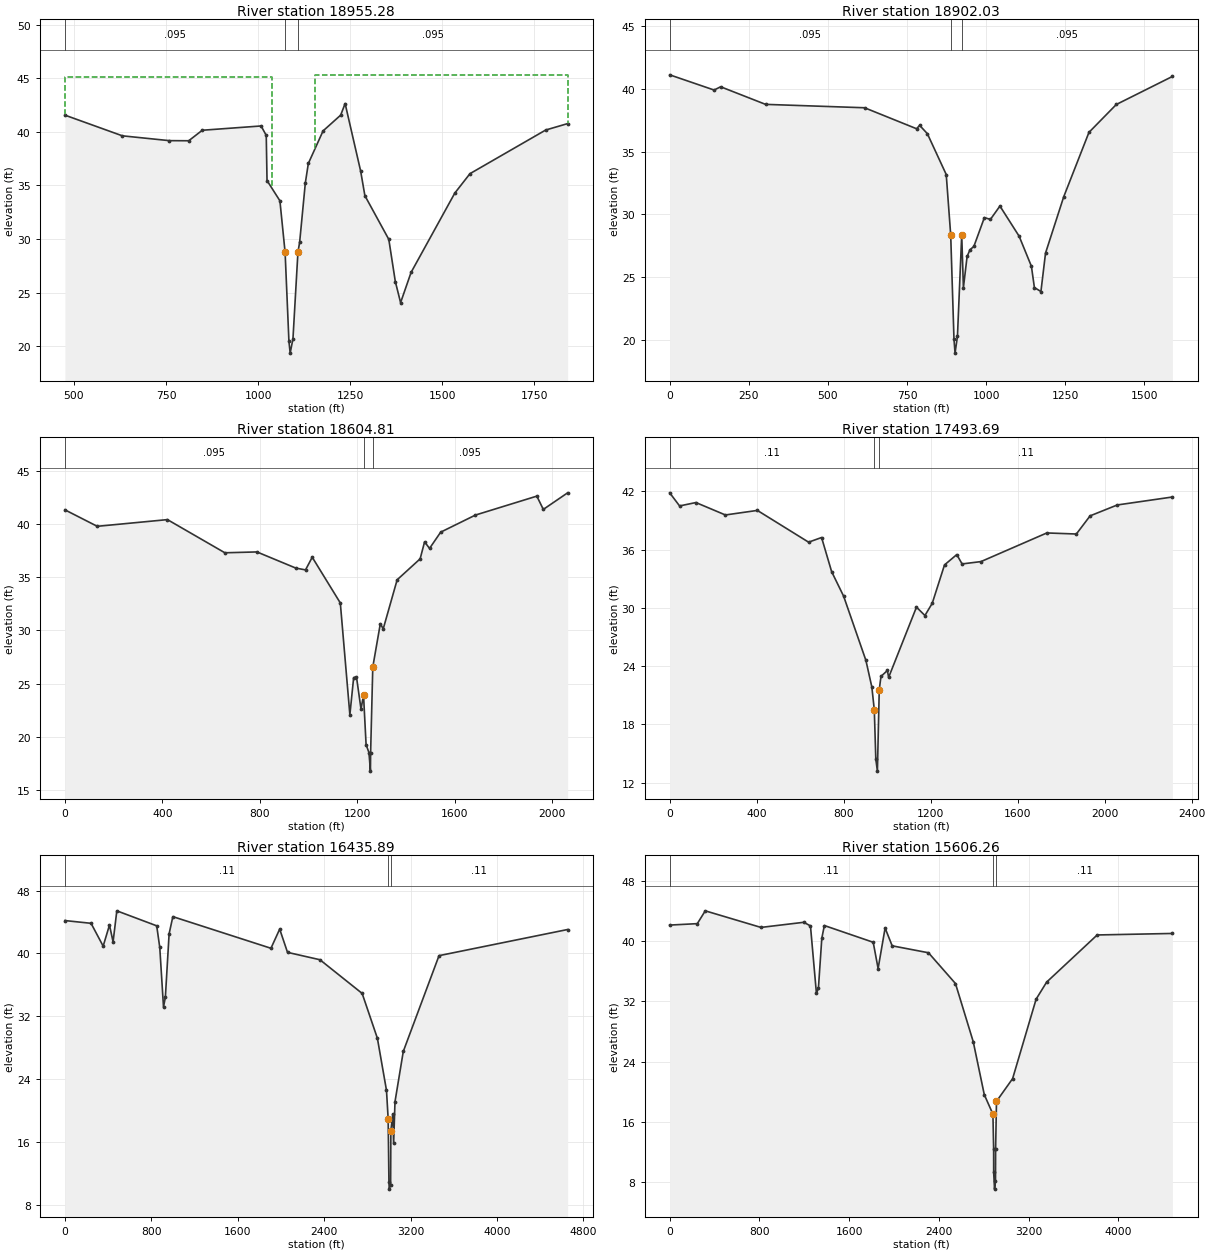
Type RM Length L Ch R = 1 ,18955.28,53.24,53.25,60
BEGIN DESCRIPTION:
copy of 441s3u;  xs 2/4 SPTC Railroad
- Channel elevations adjusted based on slope between 441v21 and 441s3
Right bank station interpolated as 13.5' beyond last survey point at elevation 28.75
Bank Station offset =      4390
Increased the Manning's value of the channel and cont/exp coeff at this location to lessen neg. delta WS
Constant of 475.45' added to cross section to allign channels for FW
END DESCRIPTION:
XS GIS Cut Line= 6
      3212468.87    13897990.924     3212570.499    13898109.278
     3212883.725    13898387.654     3213026.986    13898505.905
     3213002.694    13898993.865     3212982.808    13899107.733
#Sta/Elev= 30
  475.45   41.55  631.45   39.62  758.98   39.17  811.59   39.16  848.42   40.14
 1008.11   40.54  1022.1   39.66  1024.2   35.45 1059.18   33.56 1073.31   28.75
 1083.66   20.47 1087.04   19.35 1094.62   20.68 1108.12   28.75 1112.85   29.71
 1128.21   35.22 1136.38   37.04 1176.41   40.08  1224.2   41.55 1236.27   42.63
 1278.45   36.33 1289.91   34.04 1354.88   29.96 1372.56   26.03  1386.9   24.06
 1415.36   26.88 1534.12   34.28 1575.27   36.09 1780.81   40.16 1840.43   40.76
#Mann= 3 , 0 , 0
  475.45    .095       0 1073.31     .05       0 1108.12    .095       0
#XS Ineff= 2 , 0
  475.45 1037.45   45.11 1154.45  475.45   45.31
Permanent Ineff=
       F       F
Bank Sta=1073.31,1108.12
XS Rating Curve= 0
Exp/Cntr=.6,.4

Type RM Length L Ch R = 1 ,18902.03,177.69,297.22,347.27
BEGIN DESCRIPTION:
copy of 441s3u;  xs 1/4 SPTC Railroad
- Channel elevations adjusted based on slope between 441v21 and 441s3
Right bank station interpolated as 13.5' beyond last survey point at elevation 28.36
Bank Station offset =      4100
END DESCRIPTION:
XS GIS Cut Line= 6
     3212266.662    13897800.611     3212431.487    13898052.285
     3212906.168    13898476.564      3212979.14     13898553.75
     3212951.511    13898956.187     3212937.045    13899097.172
#Sta/Elev= 30
       0    41.1  140.36   39.89  161.04   40.15  303.02   38.75  615.95   38.48
  780.39   36.81  789.96   37.08  814.36   36.42  874.04   33.17  888.17   28.36
  898.52   20.08   901.9   18.96  909.48   20.29  922.98   28.36  928.33   24.17
  940.01   26.65  949.04   27.18   961.4   27.45  994.59   29.74 1013.74    29.6
 1043.75   30.66 1104.48   28.26 1143.26   25.87 1152.69   24.18 1173.33   23.86
  1187.9   26.92 1245.27   31.39 1325.09   36.52 1411.57   38.74 1588.86   40.97
#Mann= 3 ,-1 , 0
       0    .095       0  888.17    .045       0  922.98    .095       0
Bank Sta=888.17,922.98
XS Rating Curve= 0
Exp/Cntr=.3,.1

Type RM Length L Ch R = 1 ,18604.81,953.61,1111.12,1016.33
BEGIN DESCRIPTION:
441v21
Bank Station offset =      3746
END DESCRIPTION:
XS GIS Cut Line= 6
     3212129.875    13897669.771     3212171.506     13897955.24
     3212685.908    13898368.207     3212769.065    13898425.078
     3212733.691     13898661.08     3212611.374    13899428.031
#Sta/Elev= 30
       0   41.34  132.73   39.79  420.92   40.42  656.75    37.3   788.4   37.38
  948.15   35.86  987.91   35.69 1015.49   36.88 1130.79   32.58 1170.04   22.06
 1185.58   25.56 1197.25   25.61 1215.75    22.6 1226.12    23.9 1236.61   19.26
  1248.4    18.5 1254.48   16.76  1255.2   18.47 1264.12   26.55  1295.1   30.63
 1306.97   30.14 1364.19   34.76 1458.56   36.73 1476.84   38.33 1497.18   37.71
  1542.9   39.24 1685.82   40.85 1937.72   42.63 1964.34   41.38 2064.17   42.94
#Mann= 3 , 0 , 0
       0    .095       0 1226.12    .045       0 1264.12    .095       0
Bank Sta=1226.12,1264.12
XS Rating Curve= 0
Exp/Cntr=.3,.1

Type RM Length L Ch R = 1 ,17493.69,1050.67,1057.8,945.65
BEGIN DESCRIPTION:
441v20
Bank Station offset =      4045
END DESCRIPTION:
XS GIS Cut Line= 6
     3212004.982    13897556.772     3212028.928    13898092.288
     3212024.728    13898435.394     3211897.353    13898435.601
     3211889.904    13898520.759       3211856.3    13899739.424
#Sta/Elev= 30
       0   41.84   45.45   40.49  120.55   40.84  256.15   39.56  403.08   40.03
   638.6   36.76  698.29   37.24  744.47   33.73  799.64    31.2   902.1   24.59
  929.38   21.85  940.66   19.51  947.68   14.41  954.93   13.19  963.46   21.57
  971.37   22.94 1000.91   23.55 1006.58   22.84 1134.57   30.07 1173.45   29.21
 1207.11   30.47 1263.51   34.42  1319.8   35.48 1344.38   34.52    1431   34.76
 1733.92   37.71 1869.63    37.6 1932.91   39.47 2057.77   40.59 2311.19   41.41
#Mann= 3 , 0 , 0
       0     .11       0  940.66    .045       0  963.46     .11       0
Bank Sta=940.66,963.46
XS Rating Curve= 0
Exp/Cntr=.3,.1

Type RM Length L Ch R = 1 ,16435.89,743.51,829.63,691.5
BEGIN DESCRIPTION:
441v1819
combined v18 & v19 based on surveyed xs line
Bank Station offset =      1998
END DESCRIPTION:
XS GIS Cut Line= 6
     3212783.885    13895596.241     3211330.231    13898133.526
     3211279.173     13898223.04     3211273.634    13898226.964
     3211241.495    13898250.459     3210275.237    13899499.857
#Sta/Elev= 30
       0   44.18  241.82   43.83  354.07   40.92  412.37   43.61  445.77   41.47
  480.35   45.42  849.57   43.51  877.96   40.75  912.53   33.16  929.82   34.42
  964.39   42.49  998.97   44.68  1907.1   40.65 1987.97   43.09 2060.42   40.13
 2360.42   39.19 2751.24    34.9 2892.27   29.19 2976.64   22.55 2992.07   18.91
  2999.2   10.86 3002.31    9.97 3014.82   10.52 3017.04    17.4    3035   19.56
 3042.75   15.84 3055.28    21.1  3132.1   27.51 3462.86   39.71 4653.29   43.04
#Mann= 3 , 0 , 0
       0     .11       0 2992.07    .045       0 3017.04     .11       0
Bank Sta=2992.07,3017.04
XS Rating Curve= 0
Exp/Cntr=.3,.1

Type RM Length L Ch R = 1 ,15606.26,1898.69,1962.19,1685.06
BEGIN DESCRIPTION:
441v17
Bank Station offset =      2104
END DESCRIPTION:
XS GIS Cut Line= 4
      3212331.38    13895249.321     3210835.912    13897636.738
     3210771.501    13897753.567     3209933.104    13899035.279
#Sta/Elev= 30
       0   42.13  246.28   42.32  317.07   44.02  813.82   41.82 1195.63    42.5
 1255.16   42.02 1308.26   33.08 1325.96   33.75 1356.29   40.39 1379.06   42.07
 1814.57   39.85 1858.24   36.37 1920.62   41.74 1983.62   39.38  2307.3   38.46
 2547.99   34.38 2706.55   26.66 2805.08   19.64 2881.99   17.06 2888.34   12.41
 2888.64    9.36 2896.34    7.12 2904.89    8.22 2905.91   12.41 2913.71   18.76
 3057.44   21.77 3267.09   32.31 3361.03   34.57  3811.6   40.82  4482.1   41.02
#Mann= 3 , 0 , 0
       0     .11       0 2881.99    .045       0 2913.71     .11       0
Bank Sta=2881.99,2913.71
XS Rating Curve= 0
Exp/Cntr=.3,.1

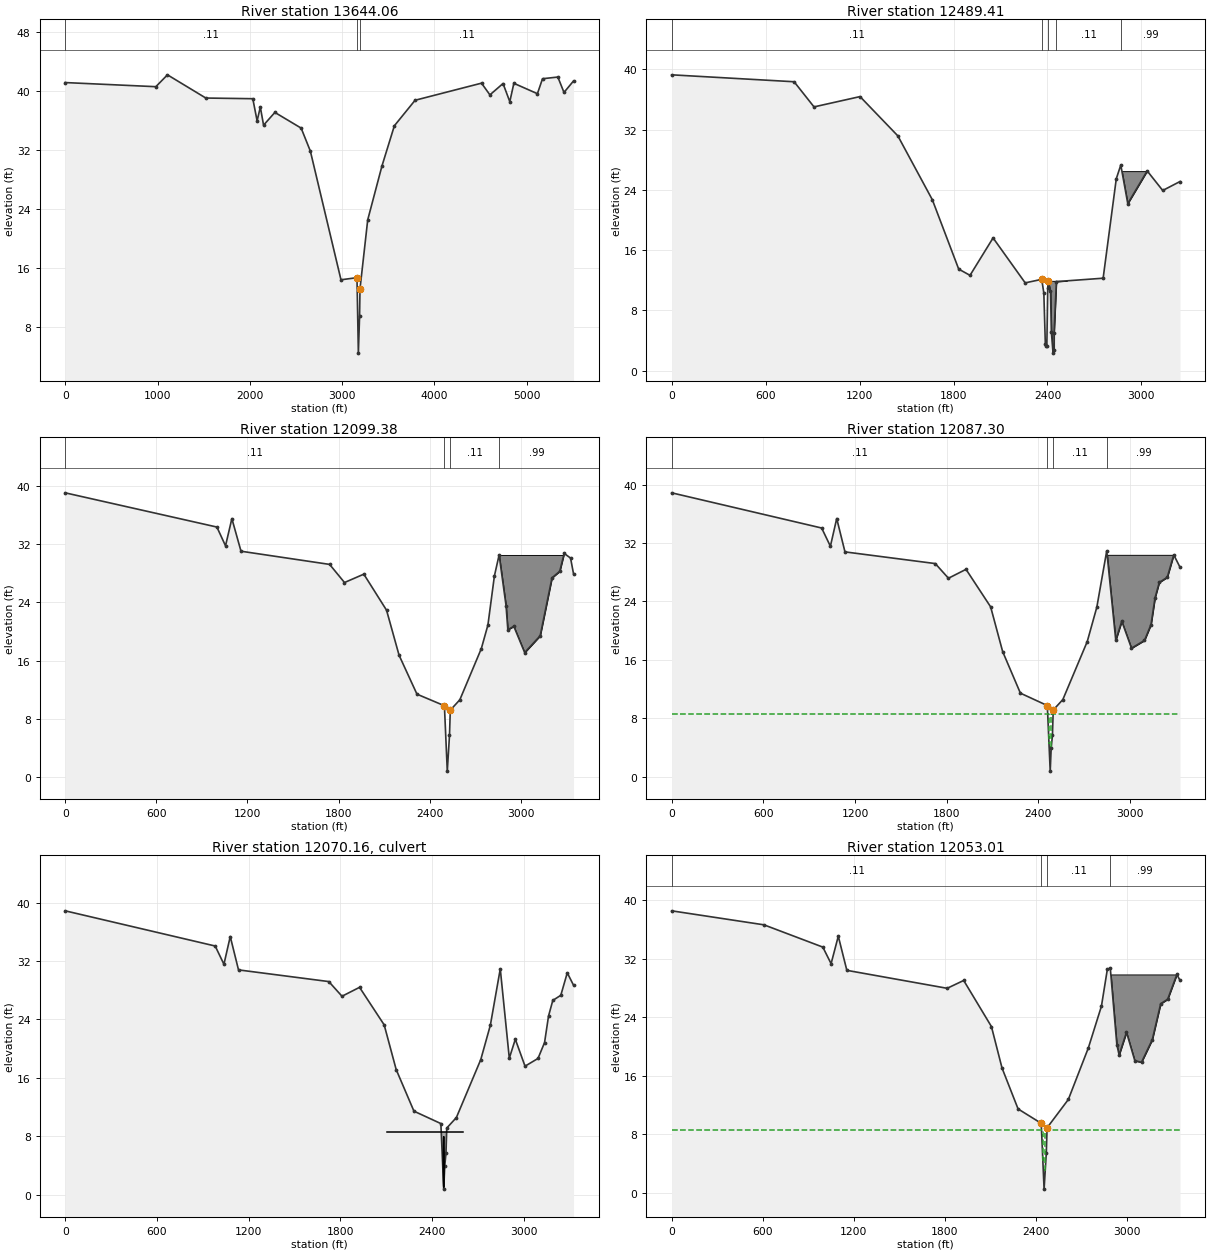
Type RM Length L Ch R = 1 ,13644.06,669.24,1154.66,996.69
BEGIN DESCRIPTION:
441v15
Bank Station offset =      1824
END DESCRIPTION:
XS GIS Cut Line= 6
     3212180.545    13895083.402     3209609.915    13896049.374
     3209628.182    13896355.563      3209638.25    13896561.773
     3209638.737    13896579.567     3209661.601    13898809.026
#Sta/Elev= 30
       0    41.1  981.77   40.54 1107.66   42.15 1523.37      39 2032.31   38.91
  2078.9    35.9 2113.84   37.78 2148.78   35.32 2271.39   37.05 2556.03   34.92
 2655.71    31.8 2987.46   14.34 3160.84   14.63 3175.74    4.39 3189.01    9.43
  3193.3   13.09 3277.12   22.47 3431.06   29.77 3565.91   35.24 3790.29    38.7
 4509.91   41.02 4600.75   39.43 4742.94   40.97 4816.34   38.51 4860.32      41
  5115.4   39.59 5170.69   41.62 5336.72   41.85 5403.37   39.76  5506.7   41.32
#Mann= 3 , 0 , 0
       0     .11       0 3160.84    .045       0  3193.3     .11       0
Bank Sta=3160.84,3193.3
XS Rating Curve= 0
Exp/Cntr=.3,.1

Type RM Length L Ch R = 1 ,12489.41,245.89,390.03,445.55
BEGIN DESCRIPTION:
REV OCT2019 to remove are protected by levee.
441v14 (442v1 added here as well)
This is a common section for both Jackson Bayou and Gum Gully. Block used for Gum Gully with n of 0.01 for Gum Gully block.
Bank Station offset =      2609
END DESCRIPTION:
XS GIS Cut Line= 6
     3210900.227    13895404.688     3208955.609    13896178.002
     3208809.643     13896348.88     3208793.216    13896437.575
     3208761.258    13896521.839     3208042.665    13896731.802
#Sta/Elev= 30
       0   39.29  782.06   38.37  909.11   35.03 1203.02    36.4 1444.55   31.18
 1664.72    22.7 1833.11   13.49 1905.36   12.66 2052.64   17.63 2257.84   11.66
 2363.42   12.13 2376.81   10.31  2386.4    3.56 2390.68    3.23 2395.88    3.26
 2401.78   10.94 2404.22   11.93 2419.38   10.54 2424.94    5.16 2435.64    2.33
 2442.24    2.74 2442.41    5.06 2456.95   11.83 2755.57   12.28 2839.57   25.49
 2868.34   27.31 2912.86   22.19  3036.9   26.53 3136.15   23.93 3246.45   25.12
#Mann= 5 ,-1 , 0
       0     .11       0 2363.42    .045       0 2404.22     .01       0
 2456.95     .11       0 2868.34     .99       0
#Block Obstruct= 2 ,-1
 2404.22    2800   11.93 2868.34  3036.9    26.5
Bank Sta=2363.42,2404.22
XS Rating Curve= 0
Exp/Cntr=.3,.1

Type RM Length L Ch R = 1 ,12099.38,12.1,12.09,12
BEGIN DESCRIPTION:
REV OCT2019 to remove are protected by levee.
441s11 copy of 441v13 -xs 4/4 --
elev adj based on slope btwn 441v12 and 441v14
xs 4/4 -- 441s11, power line culvert
Bank Station offset =      2485
END DESCRIPTION:
XS GIS Cut Line= 6
     3210781.776    13895209.032     3209585.326    13895362.612
     3208691.823    13896163.561     3208663.196    13896159.232
     3208504.673    13896144.289     3208018.639    13896718.002
#Sta/Elev= 30
       0   39.05  998.58   34.35 1055.34   31.77 1097.15   35.51 1157.31   31.03
 1740.61   29.22 1838.55   26.73 1965.76   27.88 2115.43   22.93 2197.76   16.75
 2315.59    11.4 2496.34    9.81 2515.23     .83 2529.77    5.73 2535.03     9.2
 2597.87   10.63 2739.52   17.67 2782.77    20.9 2825.37   27.63 2856.44   30.52
 2901.98   23.57 2913.84   20.25 2953.16   20.72 3024.66   17.11 3126.73   19.42
 3204.59   27.38 3255.73   28.28 3284.57   30.73 3326.68   30.09 3346.31   27.93
#Mann= 4 ,-1 , 0
       0     .11       0 2496.34    .045       0 2535.03     .11       0
 2856.44     .99       0
#Block Obstruct= 1 ,-1
 2856.44 3284.57   30.52
Bank Sta=2496.34,2535.03
XS Rating Curve= 0
Exp/Cntr=.5,.3

Type RM Length L Ch R = 1 ,12087.30,24.48,34.29,31.71
BEGIN DESCRIPTION:
REV OCT2019 to remove are protected by levee.
441s11 copy of 441v13 - elev adj based on slope btwn 441v12 and 441v14 xs 3/4 --
xs 3/4 -- 441s11, power line culvert
Bank Station offset =      2522
END DESCRIPTION:
XS GIS Cut Line= 6
     3210745.375    13895159.395     3209577.247    13895351.325
     3208682.656    13896147.154     3208516.354    13896133.234
     3208490.607    13896134.537     3208002.094    13896708.075
#Sta/Elev= 30
       0   38.88  981.72   34.06  1038.9   31.56 1080.29   35.36 1134.35   30.79
  1725.4   29.19 1811.68   27.18 1926.59    28.4  2087.8   23.26 2166.38   17.14
 2282.64   11.44 2458.85    9.74 2477.74     .76 2484.16    3.91 2492.28    5.66
 2497.54    9.13 2560.38   10.56 2720.04    18.5 2782.79   23.21 2847.75   30.93
 2906.86   18.69 2946.27   21.29  3009.8    17.6 3094.74   18.66 3137.68   20.84
 3163.72   24.48 3191.64   26.61 3243.99   27.31 3286.28   30.39 3327.27   28.69
#Mann= 4 ,-1 , 0
       0     .11       0 2458.85    .045       0 2497.54     .11       0
 2847.75     .99       0
#XS Ineff= 2 , 0
       0    2470    8.62    2485       0    8.62
Permanent Ineff=
       F       F
#Block Obstruct= 1 ,-1
 2847.75 3286.28   30.39
Bank Sta=2458.85,2497.54
XS Rating Curve= 0
Exp/Cntr=.5,.3

Type RM Length L Ch R = 2 ,12070.16,,,
BEGIN DESCRIPTION:
441s11, Power line culvert S. of Newport WWTP
Culvert length and road width estimated from Mr.Sids
"Road" ended early as upstream and downstream sections cross the road.
END DESCRIPTION:
Bridge Culvert--1,0,-1,-1, 0
Deck Dist Width WeirC Skew NumUp NumDn MinLoCord MaxHiCord MaxSubmerge Is_Ogee
5.15,24,2.6,0, 2, 2, , , .95, 0, 0,0,,
 2103.11 2603.11
    8.62    8.62
       0       0
 2091.11 2591.11
    8.99    8.99
       0       0
BR Coef=-1 , 0 , 0 ,, 0 ,,,.8,0,,0,
WSPro=,,,, 1 ,,,, 0 ,,,, 0 ,,,,-1 ,-1 ,-1 , 0 , 0 , 0 , 0 , 0
Culvert=1,7,,30,.015,.5,1,55,1,.99,2477.74,.62,2454.49,441s11      , 0 ,2.15
Culvert Bottom n=.015
BC Design=,, 0 ,, 0 ,,,,,,
BC HTab HWMax=38.88

Type RM Length L Ch R = 1 ,12053.01,12.57,20.07,19.86
BEGIN DESCRIPTION:
REV OCT2019 to remove are protected by levee.
441s11 copy of 441v13 -xs 2/4 -- SURVEY HERE
xs 2/4 -- 441s11, power line culvert
Bank Station offset =      2546
END DESCRIPTION:
XS GIS Cut Line= 6
     3210732.138    13895113.067     3209547.464    13895324.852
     3208684.759    13896114.912     3208520.045    13896100.193
     3208475.301    13896105.811     3207988.857    13896698.148
#Sta/Elev= 30
       0   38.51  608.19    36.6  996.19   33.56 1050.71    31.3 1098.12   35.05
 1154.52   30.39 1815.65   27.94 1924.59   29.01 2107.43   22.72 2177.15   17.07
 2283.09   11.48  2435.6    9.52 2454.49     .54 2469.03    5.44 2474.29    8.91
 2614.25   12.77 2746.42   19.82 2832.46    25.5 2871.28   30.52 2890.69   30.71
 2933.91   20.27 2948.92   18.84 2997.59   21.95 3052.46   18.06 3096.48   17.85
 3167.56   20.93 3222.86   25.83 3269.12   26.45  3329.6   29.83 3350.21   29.02
#Mann= 4 ,-1 , 0
       0     .11       0  2435.6    .045       0 2474.29     .11       0
 2890.69     .99       0
#XS Ineff= 2 , 0
       0 2446.75    8.62 2461.75       0    8.62
Permanent Ineff=
       F       F
#Block Obstruct= 1 ,-1
 2890.69  3329.6   29.83
Bank Sta=2435.6,2474.29
XS Rating Curve= 0
Exp/Cntr=.5,.3