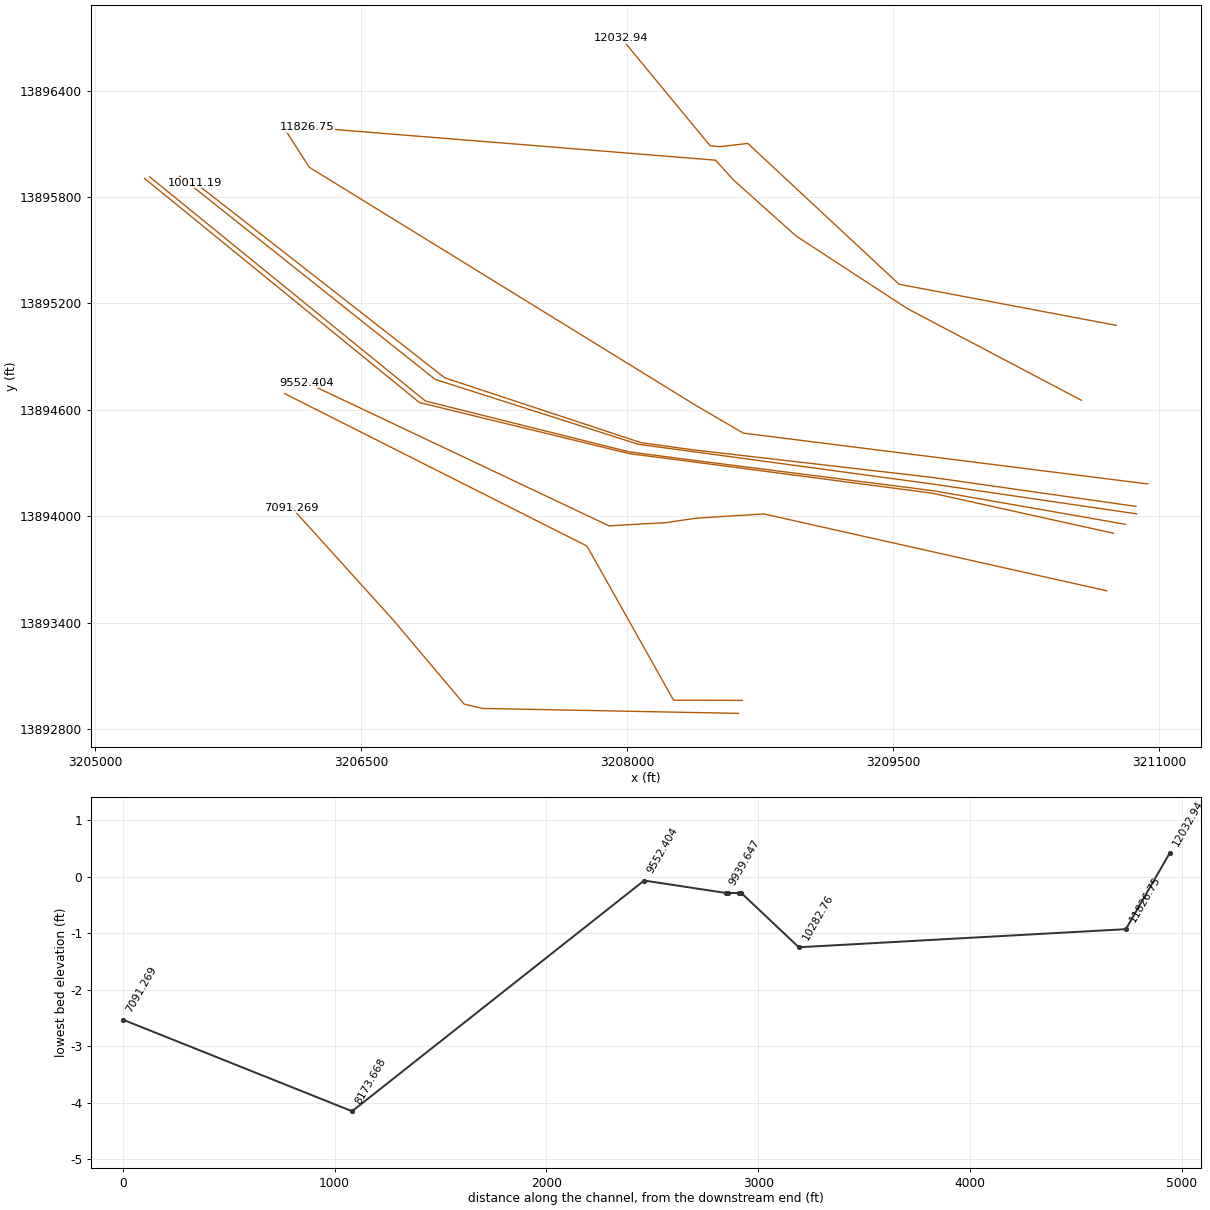
HEC-RAS study R100-00-00.prj: R100-00-00

--- R100-00-00.g01 (geometry) --- (continued)

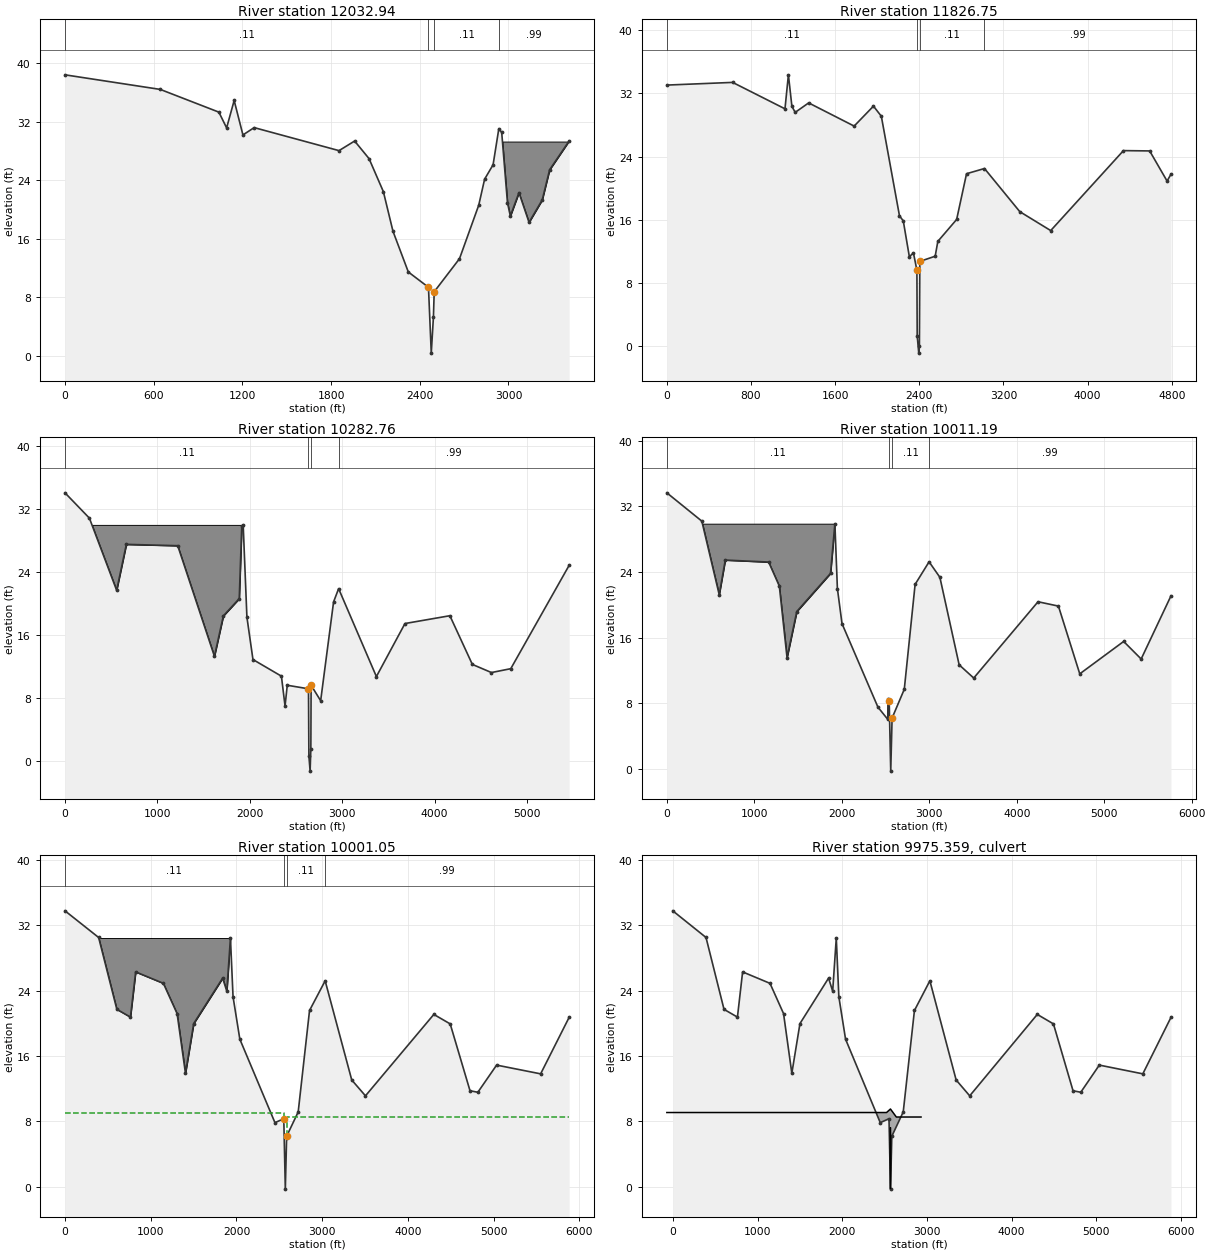
Type RM Length L Ch R = 1 ,12032.94,207.35,206.2,173.2
BEGIN DESCRIPTION:
REV OCT2019 to remove are protected by levee.
441s11 copy of 441v13 - elev adj based on slope btwn 441v12 and 441v14 xs 1/4 --
xs 1/4 -- 441s11, power line culvert
Bank Station offset =      2522
END DESCRIPTION:
XS GIS Cut Line= 6
     3210758.612    13895076.666     3209534.228    13895308.307
     3208681.254    13896102.295     3208522.148    13896084.072
     3208468.683    13896089.265     3207969.002    13896694.838
#Sta/Elev= 30
       0   38.37  644.58   36.38 1040.96   33.28 1093.38   31.13 1144.33   34.87
 1203.72   30.17 1279.66   31.17 1853.62   28.03 1959.39   29.34 2056.81   26.94
 2153.67   22.44 2218.79   17.03 2322.51   11.48  2458.9    9.39 2477.79     .41
 2492.33    5.31 2497.59    8.78 2668.73   13.29 2798.94   20.59 2838.68   24.14
 2895.95    26.1 2934.84   31.03 2954.29   30.51 2993.19   20.94 3012.63    19.1
 3070.98    22.3 3139.13   18.25 3228.27    21.3 3278.47   25.42  3410.4   29.35
#Mann= 4 ,-1 , 0
       0     .11       0  2458.9    .045       0 2497.59     .11       0
 2934.84     .99       0
#Block Obstruct= 1 ,-1
 2934.84 3401.03   29.27
Bank Sta=2458.9,2497.59
XS Rating Curve= 0
Exp/Cntr=.3,.1

Type RM Length L Ch R = 1 ,11826.75,1543.22,1543.98,1443.79
BEGIN DESCRIPTION:
441v12
Bank Station offset =      2605
Block added in right overbank to keep flow within main part of cross section
END DESCRIPTION:
XS GIS Cut Line= 6
     3210561.815    13894654.202     3209581.004    13895170.993
     3208952.781     13895580.87     3208599.394     13895897.49
     3208499.768    13896007.864     3206195.877    13896193.608
#Sta/Elev= 30
       0   33.06  625.54    33.4 1123.21   30.05 1155.72   34.36 1188.99   30.36
 1220.41    29.6 1348.39    30.8 1780.89   27.86 1964.42   30.39 2039.23   29.11
 2211.84   16.48 2247.99   15.84 2305.62    11.3 2344.69   11.77 2377.47    9.58
 2380.33    1.26 2395.21    -.93 2401.28    -.06 2405.31    10.7 2551.33   11.36
 2576.55   13.24 2755.42   16.02 2849.45   21.82 3020.05   22.48 3355.78   17.01
 3649.76   14.61 4341.38   24.75 4590.63   24.71 4756.17   20.89 4793.28   21.76
#Mann= 4 ,-1 , 0
       0     .11       0 2377.47    .045       0 2405.31     .11       0
 3020.05     .99       0
#Block Obstruct= 2 , 0
       0                 4455.19       0   24.95
Bank Sta=2377.47,2405.31
XS Rating Curve= 0
Exp/Cntr=.3,.1

Type RM Length L Ch R = 1 ,10282.76,144.05,271.57,321.19
BEGIN DESCRIPTION:
441v11
Bank Station offset =      2347
Block in left overbank from the railroad in the left overbank.
END DESCRIPTION:
XS GIS Cut Line= 6
     3210936.694    13894182.443     3208655.694    13894469.168
     3208383.367    13894628.069     3208307.439    13894675.202
     3206208.898    13895967.914     3206052.648    13896210.969
#Sta/Elev= 30
       0   34.01  264.31    30.8  559.05   21.66  664.18   27.48 1220.28   27.31
 1617.61    13.3 1714.36   18.42 1886.22   20.61 1913.77   29.78 1928.88   29.95
 1969.19   18.27 2034.71   12.89 2342.74   10.78 2382.06       7  2406.1    9.63
 2635.88    9.18 2640.15     .68 2653.41   -1.25 2661.39     1.6 2664.23    9.63
 2767.56    7.67 2907.45   20.19 2961.95   21.87 3370.89   10.73 3680.27   17.45
 4166.37   18.44 4409.69   12.27 4616.41   11.24 4825.67   11.73 5457.31   24.82
#Mann= 4 ,-1 , 0
       0     .11       0 2635.88    .045       0 2664.23     .11       0
 2961.95     .99       0
#Block Obstruct= 2 , 0
       0 1928.88   29.95               0
Bank Sta=2635.88,2664.23
XS Rating Curve= 0
Exp/Cntr=.3,.1

Type RM Length L Ch R = 1 ,10011.19,10.2,10.14,10
BEGIN DESCRIPTION:
copy of 441s2d; xs 4/4 Dirt Road
elevations not adjusted due to adverse slope btwn 441v11 & 441v10
Bank Station offset =      2440
Block in left overbank from the railroad in the left overbank. (Right overbank high localized in the "dirt road" area.)
END DESCRIPTION:
XS GIS Cut Line= 6
       3210869.3    13894056.079     3209716.791    13894219.897
     3208364.021    13894375.913     3208080.407    13894415.019
     3206973.079    13894780.565     3205566.227    13895879.932
#Sta/Elev= 30
       0   33.64   399.7   30.19  598.73   21.22  668.08   25.44 1164.09    25.2
  1285.9   22.27 1374.09   13.55 1485.56   19.17 1871.23   23.82 1921.19   29.88
 1949.75   21.97 2002.65   17.69  2413.4    7.51 2525.83    6.02 2527.77    8.46
 2541.79    8.32 2559.67    -.29 2575.16    6.18 2714.59    9.69 2838.38   22.48
 2998.01   25.23  3121.6   23.34  3341.8   12.67 3508.51   11.06 4243.72   20.36
  4476.9   19.83 4720.76   11.57 5222.78   15.52 5422.74   13.38 5763.69   21.08
#Mann= 4 ,-1 , 0
       0     .11       0 2541.79     .04       0 2575.16     .11       0
 2998.01     .99       0
#Block Obstruct= 2 , 0
       0 1921.19   29.88               0
Bank Sta=2541.79,2575.16
XS Rating Curve= 0
Exp/Cntr=.5,.3

Type RM Length L Ch R = 1 ,10001.05,46.12,51.38,52.35
BEGIN DESCRIPTION:
copy of 441s2d; xs 3/4 Dirt Road
elevations not adjusted due to adverse slope btwn 441v11 & 441v10
Bank Station offset =      2430
Block in left overbank from the railroad in the left overbank. (Right overbank high localized in the "dirt road" area.)
END DESCRIPTION:
XS GIS Cut Line= 6
     3210873.512    13894013.958     3209704.148    13894184.701
     3208364.069    13894365.723     3208064.075    13894406.082
     3206918.321    13894772.141     3205477.773    13895917.841
#Sta/Elev= 30
       0   33.75  392.28   30.49  604.75    21.7  763.25   20.75  824.29   26.28
 1147.46   24.88 1307.43   21.18 1405.18   13.88 1501.11   19.96 1838.81   25.52
 1887.35   23.92 1929.77   30.43 1960.05   23.24 2039.29   18.05  2448.8    7.84
 2551.97    8.32 2569.85    -.29 2585.34    6.18 2719.96    9.15 2852.26   21.56
 3034.42   25.19 3344.52   13.06 3504.62   11.12 4302.01   21.08 4492.85   19.92
 4724.13   11.74 4815.63   11.56  5034.3   14.88 5547.79   13.81 5880.12   20.72
#Mann= 4 ,-1 , 0
       0     .11       0 2551.97     .04       0 2585.34     .11       0
 3034.42     .99       0
#XS Ineff= 2 , 0
       0 2551.97    9.08 2585.34       0    8.53
Permanent Ineff=
       F       F
#Block Obstruct= 2 , 0
       0 1929.77   30.43               0
Bank Sta=2551.97,2585.34
XS Rating Curve= 0
Exp/Cntr=.5,.3

Type RM Length L Ch R = 2 ,9975.359,,,
BEGIN DESCRIPTION:
441s2, 7.5 ft metal culvert
END DESCRIPTION:
Bridge Culvert--1,0,-1,-1, 0
Deck Dist Width WeirC Skew NumUp NumDn MinLoCord MaxHiCord MaxSubmerge Is_Ogee
16.7,18,2.6,0, 5, 5, , , .95, 0, 0,0,,
  -69.91 2522.98 2569.09 2638.74 2930.09
    9.08    9.08    9.51    8.53    8.53
       0       0       0       0       0
 -165.98 2472.91 2519.02 2588.67 2834.02
    9.08    9.08    9.51    8.53    8.53
       0       0       0       0       0
BR Coef=-1 , 0 , 0 ,, 0 ,,,.8,0,,0,
WSPro=,,,, 1 ,,,, 0 ,,,, 0 ,,,,-1 ,-1 ,-1 , 0 , 0 , 0 , 0 , 0
Culvert=1,7.5,,38.2,.016,.5,1,55,1,-.25,2569.09,-.01,2519.02,441s2       , 0 ,6.59
Culvert Bottom n=.016
BC Design=,, 0 ,, 0 ,,,,,,
BC HTab HWMax=33.75

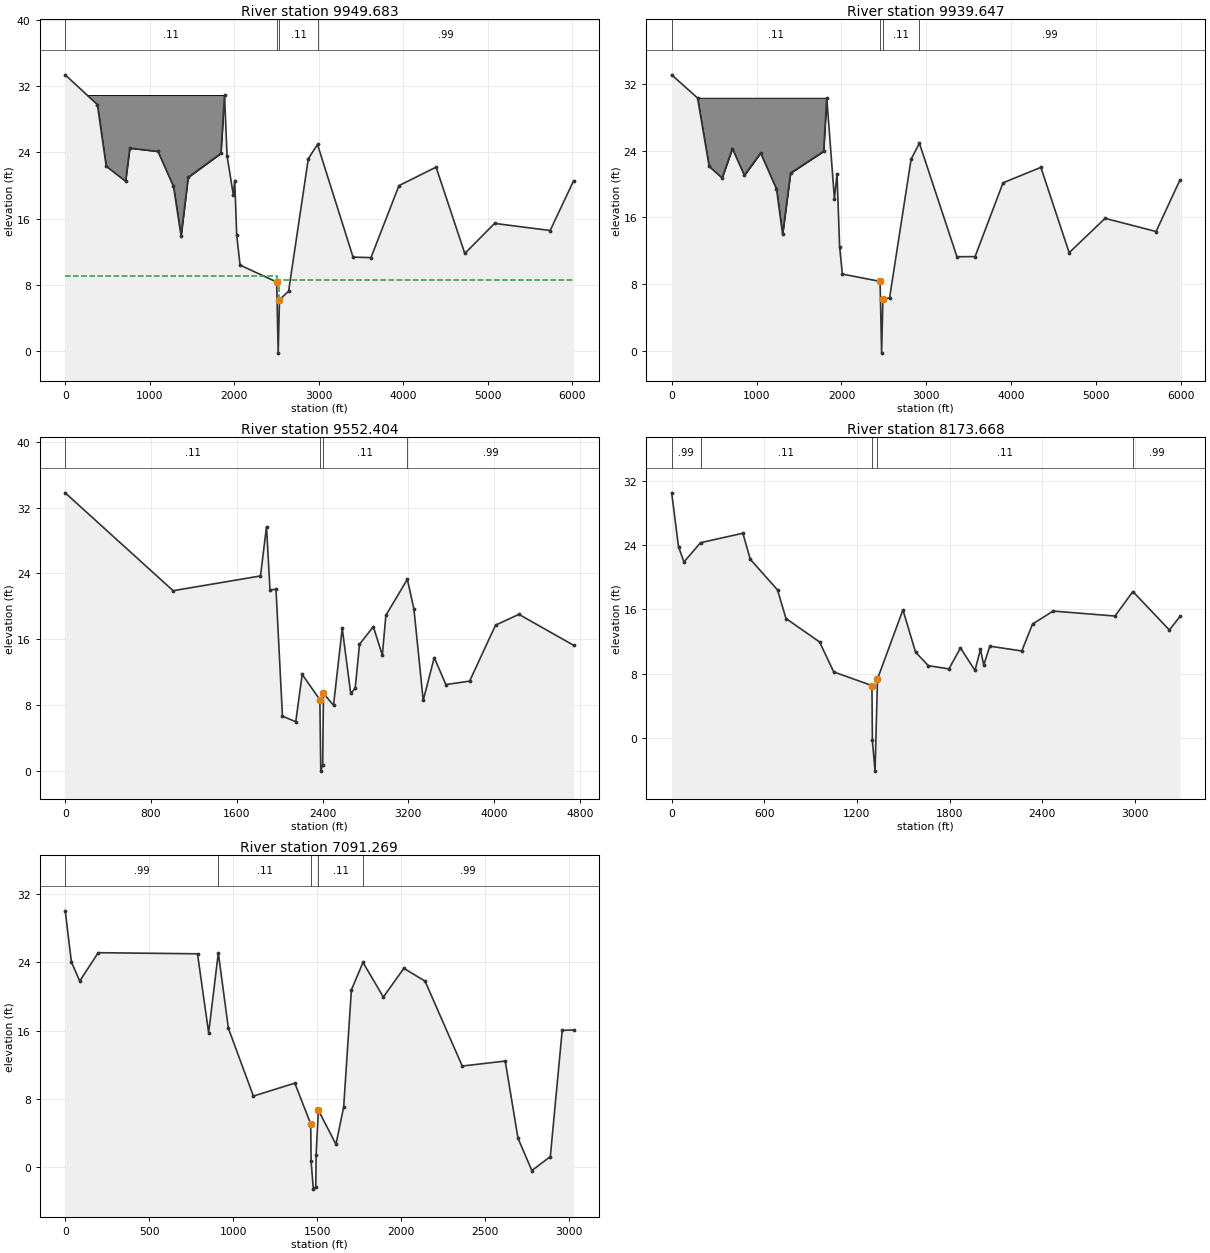
Type RM Length L Ch R = 1 ,9949.683,10,10.03,11.16
BEGIN DESCRIPTION:
441s2d;  xs 2/4 Dirt Road (survey here)
Bank Station offset =      2480
Block in left overbank from the railroad in the left overbank. (Right overbank high localized in the "dirt road" area.)
END DESCRIPTION:
XS GIS Cut Line= 6
      3210810.33    13893954.988     3209729.187    13894144.009
        3208343.    13894320.022     3208013.428    13894363.204
     3206863.564    13894649.989     3205309.287    13895913.629
#Sta/Elev= 30
       0   33.39  380.65   29.79  484.94   22.33  714.39   20.51  763.87   24.52
 1097.54   24.12 1281.21   19.88 1371.04   13.89 1454.71   20.99 1842.39   23.89
 1885.13   30.94 1915.37   23.59 1989.26   18.87  2006.1    20.6 2029.53   13.99
  2069.4   10.36 2502.44    8.32 2520.32    -.29 2535.81    6.18 2643.38     7.2
 2877.13   23.25 2985.75   24.96 3406.58   11.33 3618.35   11.27 3949.42   19.98
 4388.97   22.22 4728.84   11.77 5081.18   15.41 5738.92   14.55 6015.47   20.55
#Mann= 4 ,-1 , 0
       0     .11       0 2502.44     .04       0 2535.81     .11       0
 2985.75     .99       0
#XS Ineff= 2 , 0
       0 2502.44    9.08 2535.81       0    8.53
Permanent Ineff=
       F       F
#Block Obstruct= 2 , 0
       0 1885.13   30.94               0
Bank Sta=2502.44,2535.81
XS Rating Curve= 0
Exp/Cntr=.5,.3

Type RM Length L Ch R = 1 ,9939.647,285.02,387.24,430.71
BEGIN DESCRIPTION:
copy of 441s2d;  xs 1/4 Dirt Road
elevations not adjusted due to adverse slope btwn 441v11 & 441v10
Bank Station offset =      2528
Block in left overbank from the railroad in the left overbank. (Right overbank high localized in the "dirt road" area.)
END DESCRIPTION:
XS GIS Cut Line= 6
     3210742.936    13893904.442     3209720.545    13894130.626
     3208257.398    13894322.086     3208014.299    13894353.158
     3206829.867    13894641.565     3205279.803    13895905.204
#Sta/Elev= 30
       0   33.12   304.7   30.34  441.02   22.13  593.75   20.74  714.85   24.27
  855.26   21.06 1047.11   23.74 1234.48   19.41 1306.27   13.96 1399.98   21.33
 1789.14   23.94 1826.36   30.37 1916.94   18.24 1947.39   21.25 1977.64   12.51
 2010.41     9.2 2454.56    8.32 2472.44    -.29 2487.93    6.18 2566.38    6.34
 2819.78   22.99 2917.43   24.91 3359.82   11.28  3573.1    11.3 3902.81   20.16
    4348   22.01  4681.5   11.77 5104.57   15.89 5704.91   14.31 5986.72   20.51
#Mann= 4 ,-1 , 0
       0     .11       0 2454.56     .04       0 2487.93     .11       0
 2917.43     .99       0
#Block Obstruct= 2 , 0
       0 1826.36   30.37               0
Bank Sta=2454.56,2487.93
XS Rating Curve= 0
Exp/Cntr=.3,.1

Type RM Length L Ch R = 1 ,9552.404,1171.22,1378.74,339.26
BEGIN DESCRIPTION:
441v10
Bank Station offset =      2616
Right overbank not extended because flow from here down will not enter Jackson bayou again, but will flow directly into San Jacinto.
END DESCRIPTION:
XS GIS Cut Line= 6
     3210705.027    13893580.108     3208771.418    13894013.562
     3208389.418    13893989.404     3208222.229    13893964.555
     3207898.923    13893946.294     3206195.877    13894752.636
#Sta/Elev= 30
       0   33.82  1006.8    21.9 1821.39    23.7 1877.63    29.7 1910.11   22.02
 1966.19   22.07 2026.38    6.62 2150.48    5.95  2210.6   11.71 2375.49    8.62
 2383.75    -.07 2401.39     .68 2409.11     9.4 2502.63    7.95 2584.05   17.32
 2662.95    9.42 2704.87   10.01 2744.97   15.37 2874.13   17.53 2957.95   14.05
 2991.14    18.9 3191.33   23.29 3252.49   19.69 3339.46    8.55 3442.27   13.76
 3550.88   10.47 3772.21   10.89 4014.03   17.71 4232.19   19.02  4741.5   15.26
#Mann= 4 ,-1 , 0
       0     .11       0 2375.49     .04       0 2409.11     .11       0
 3191.33     .99       0
#Block Obstruct= 2 , 0
       0                  4534.6       0      21
Bank Sta=2375.49,2409.11
XS Rating Curve= 0
Exp/Cntr=.3,.1

Type RM Length L Ch R = 1 ,8173.668,768.22,1082.4,1118.27
BEGIN DESCRIPTION:
441v9
Bank Station offset =      3682
Right overbank  not extended because flow from here down will not enter Jackson bayou again, but will flow directly into San Jacinto.
END DESCRIPTION:
XS GIS Cut Line= 5
     3208650.277    13892962.322     3208262.416    13892963.305
     3207828.834     13893735.87     3207774.048    13893832.552
     3206070.009    13894691.872
#Sta/Elev= 30
       0    30.5   44.27    23.8   79.61   21.89  186.93   24.29  461.29   25.47
  509.18   22.23   685.7   18.41  740.65   14.85  958.03   11.94 1049.93     8.2
 1297.58     6.5 1300.38    -.32 1317.75   -4.15 1333.48    7.33 1498.22   15.93
 1580.42   10.65 1663.24    8.98 1796.35    8.58  1870.9   11.19 1965.12    8.39
 2000.82   11.02 2021.77    9.05 2061.18   11.41 2268.38   10.81 2337.85   14.16
 2471.22   15.78 2872.16   15.16 2988.26   18.21  3224.6   13.42 3293.35   15.11
#Mann= 5 ,-1 , 0
       0     .99       0  186.93     .11       0 1297.58     .04       0
 1333.48     .11       0 2988.26     .99       0
#Block Obstruct= 2 , 0
       0                 2988.26       0      21
Bank Sta=1297.58,1333.48
XS Rating Curve= 0
Exp/Cntr=.3,.1

Type RM Length L Ch R = 1 ,7091.269,971.79,808.58,633.66
BEGIN DESCRIPTION:
441v8
Bank Station offset =      3523
Right overbanknot extended because flow from here down will not enter Jackson bayou again, but will flow directly into San Jacinto.
END DESCRIPTION:
XS GIS Cut Line= 5
     3208628.759    13892889.024     3207184.267    13892916.942
     3207081.658    13892941.657     3206681.044    13893416.786
     3206109.071    13894049.511
#Sta/Elev= 30
       0   29.98   36.99   23.99   86.49   21.78  196.44   25.09  787.24   24.96
  853.56   15.72  911.06   25.07  970.95   16.26 1119.78    8.34 1366.21    9.85
 1460.94    5.09 1463.22      .7  1476.6   -2.53 1491.06   -2.24 1492.98    1.48
 1506.51    6.69 1611.16     2.7 1657.02    7.08    1703   20.75 1771.84   23.95
 1893.07   19.91 2014.98   23.26 2141.28   21.77 2362.54   11.85 2618.31   12.43
 2694.32    3.42 2776.72    -.36 2886.64    1.27 2957.26   16.01 3024.72   16.06
#Mann= 5 ,-1 , 0
       0     .99       0  911.06     .11       0 1460.94    .045       0
 1506.51     .11       0 1771.84     .99       0
#Block Obstruct= 2 , 0
       0                    3023       0      20
Bank Sta=1460.94,1506.51
XS Rating Curve= 0
Exp/Cntr=.3,.1