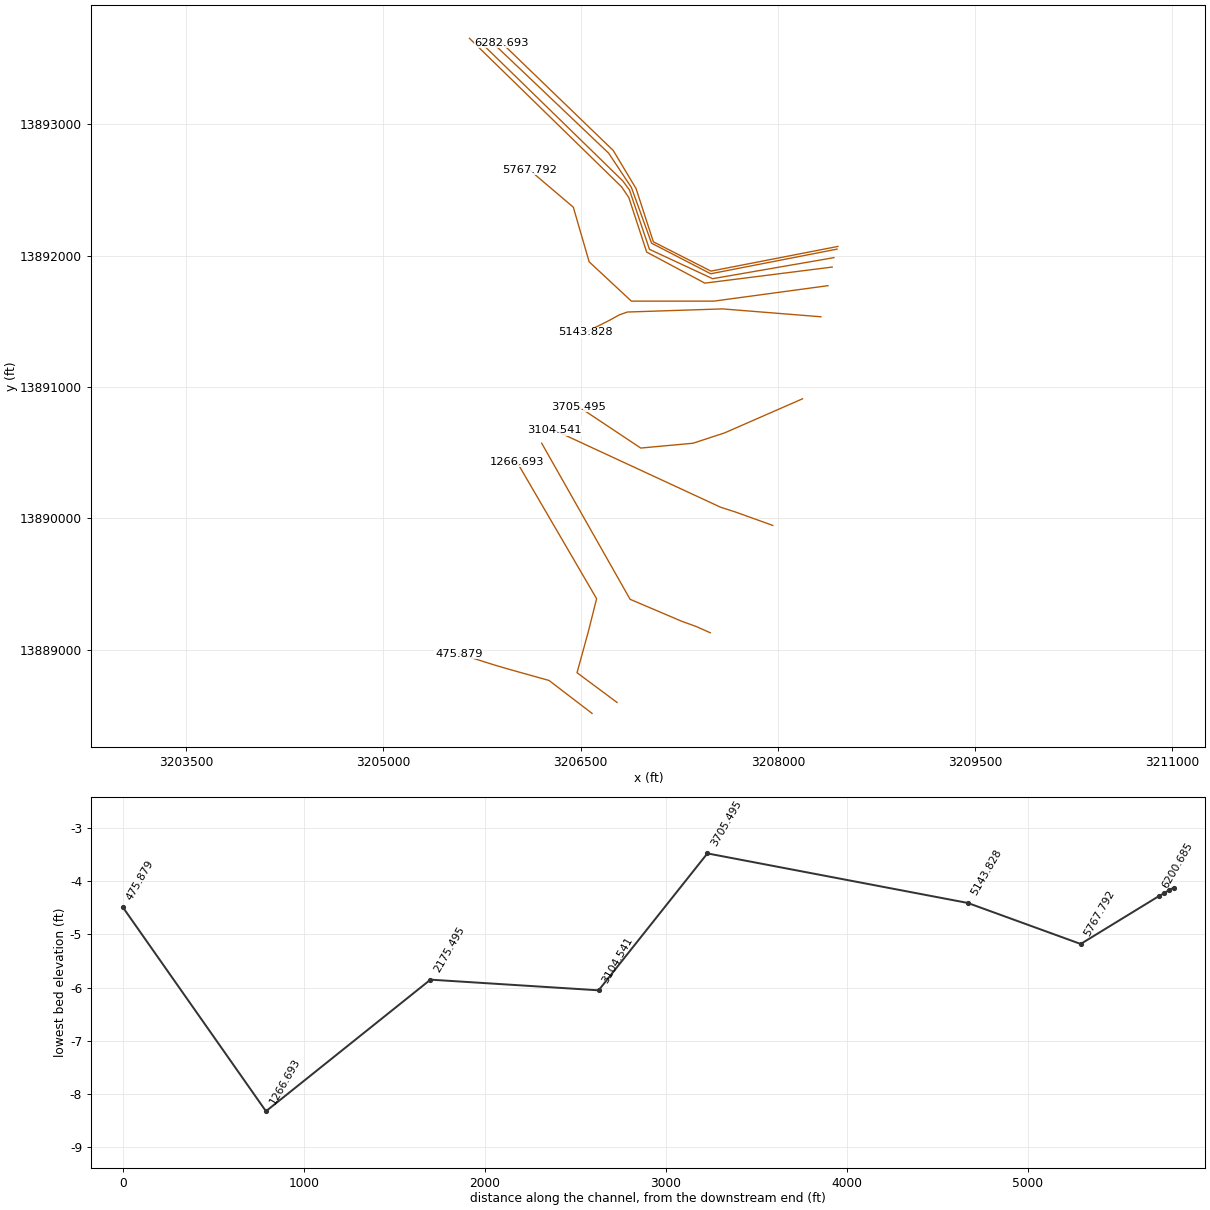
HEC-RAS study R100-00-00.prj: R100-00-00

--- R100-00-00.g01 (geometry) --- (continued)

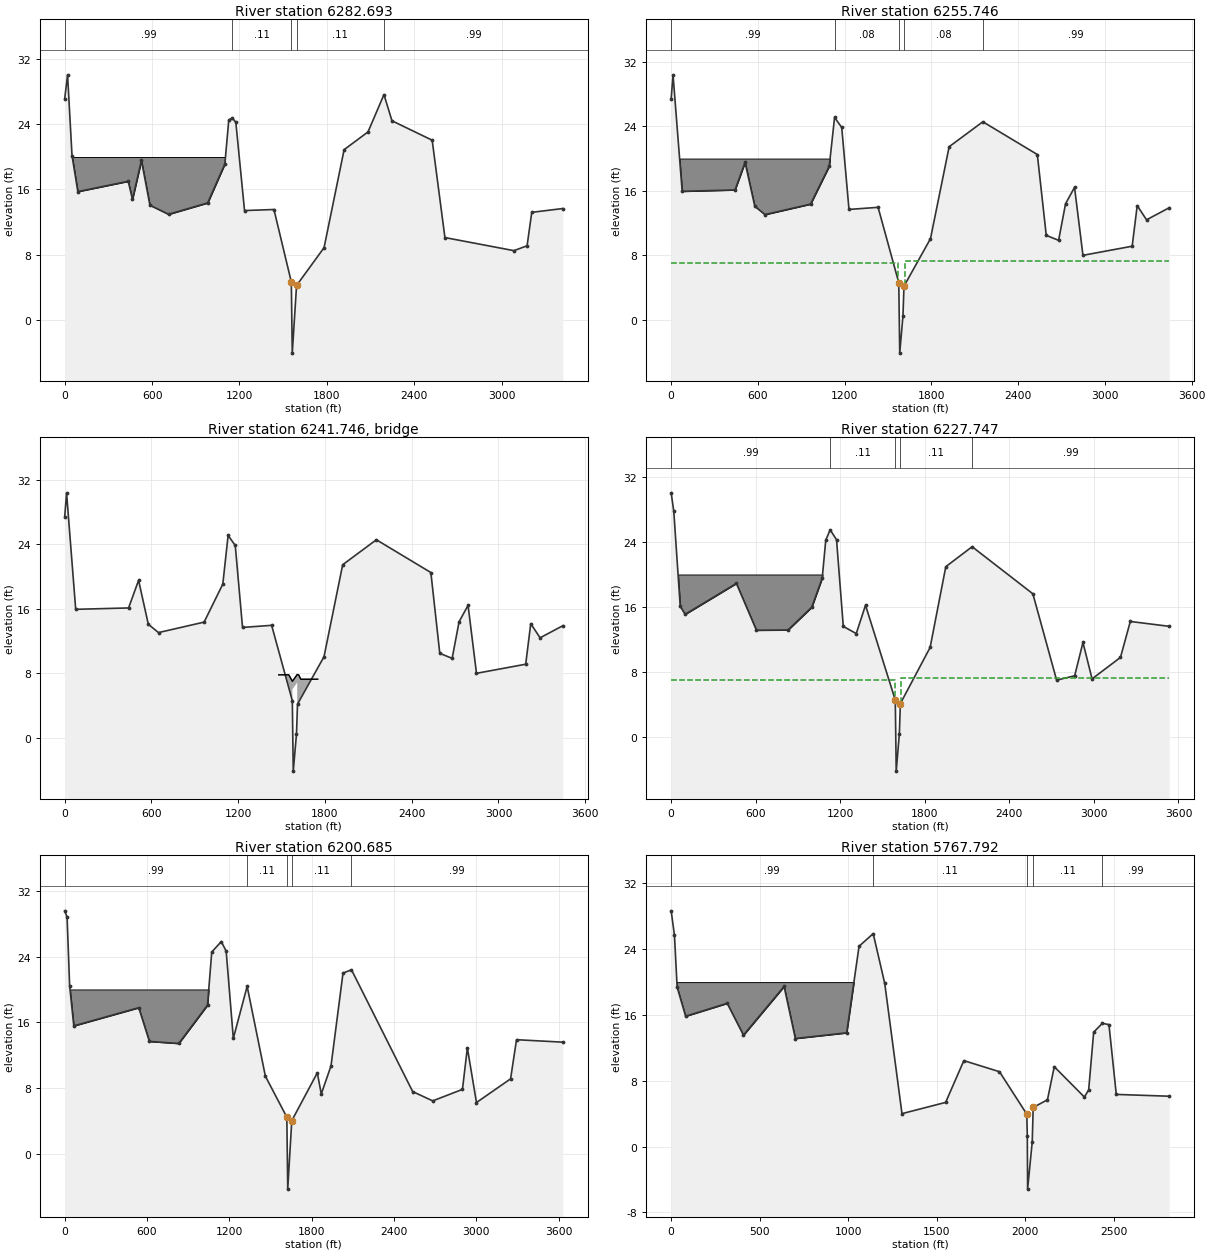
Type RM Length L Ch R = 1 ,6282.693,17.98,26.95,28
BEGIN DESCRIPTION:
441s1u;  xs 4/4 Gravel Pit Road (survey here)
Bank Station offset =      3438
Right overbank not extended because flow from here down will not enter Jackson bayou again, but will flow directly into San Jacinto.  Block in left overbank at watershed divide.  Manning's and Cont/exp increased to lessen negative slope in profile.
END DESCRIPTION:
XS GIS Cut Line= 6
     3208457.195    13892069.061     3207491.022    13891881.303
     3207053.318    13892104.036     3206921.788    13892508.712
     3206748.499    13892798.372     3205898.986    13893618.017
#Sta/Elev= 30
       0   27.15   19.69    30.1   50.25   20.17    90.2   15.74  436.24   17.01
  465.16   14.78  526.77   19.57  585.07   14.07  713.08   12.95  981.62   14.35
 1099.65   19.14 1126.48   24.56 1151.79   24.77 1174.96   24.25 1234.63   13.41
 1436.59   13.54 1555.82    4.63 1562.38   -4.12 1591.81     4.2 1780.71    8.85
 1918.33    20.9 2082.38   23.08 2191.92   27.67 2246.75   24.45  2522.9   22.06
 2610.39   10.09 3084.14    8.48 3174.47    9.08 3206.49   13.19 3419.39   13.66
#Mann= 5 ,-1 , 0
       0     .99       0 1151.79     .11       0 1555.82     .05       0
 1591.81     .11       0 2191.92     .99       0
#Block Obstruct= 2 , 0
       0    1100      20    3418       0      20
Bank Sta=1555.82,1591.81
XS Rating Curve= 0
Exp/Cntr=.8,.6

Type RM Length L Ch R = 1 ,6255.746,28,28,28
BEGIN DESCRIPTION:
copy of 441s1u;  xs 3/4 Gravel Pit Road
Bank Station offset =      3419
Channel elevations adjusted based on slope between 441v7 and 441v8.  Right overbank not extended because flow from here down will not enter Jackson bayou again, but will flow directly into San Jacinto.  Block in left overbank at watershed divide.
 Cont/exp increased to lessen negative slope in profile; Also overbank manning's n decreased, but channel's increased
END DESCRIPTION:
XS GIS Cut Line= 6
     3208450.572    13892048.575     3207489.405    13891861.155
     3207039.472    13892093.652      3206886.52      13892517.2
     3206713.431    13892778.006      3205848.44    13893601.169
#Sta/Elev= 30
       0    27.4   12.94    30.4   76.12   15.93  441.85    16.1  511.02   19.53
  578.39   14.07  648.93   13.04  964.14   14.34 1093.56   19.06 1130.23   25.11
 1179.74   23.86 1229.97   13.68 1431.24   13.94 1574.29    4.58 1580.85   -4.17
  1603.2     .45 1610.28    4.15 1793.64   10.05 1922.72   21.47 2155.74   24.57
 2532.59    20.5 2594.28   10.46 2679.82    9.84 2727.78   14.39 2789.91   16.42
  2848.1    7.98  3188.5    9.11  3223.4   14.15 3287.97   12.39 3444.83   13.89
#Mann= 5 ,-1 , 0
       0     .99       0 1130.23     .08       0 1574.29     .06       0
 1610.28     .08       0 2155.74     .99       0
#XS Ineff= 2 , 0
       0    1570    6.99    1615       0    7.25
Permanent Ineff=
       F       F
#Block Obstruct= 2 , 0
       0    1100      20    3443       0      20
Bank Sta=1574.29,1610.28
XS Rating Curve= 0
Exp/Cntr=.8,.6

Type RM Length L Ch R = 3 ,6241.746,,,
BEGIN DESCRIPTION:
441s1, gravel pit road
Road ended early as upstream and downstream sections cross the road.
END DESCRIPTION:
Bridge Culvert--1,0,-1,-1, 0
Deck Dist Width WeirC Skew NumUp NumDn MinLoCord MaxHiCord MaxSubmerge Is_Ogee
4.5,19,2.6,0, 9, 9, , , .95, 0, 0,0,,
 1480.91 1550.11 1565.63 1574.64  1590.9 1608.08 1618.55  1632.8    1750
    7.79    7.79    7.29    6.99    7.39    7.83    7.78    7.25    7.25
                            5.99    6.39    6.83
 1496.66 1565.86 1581.38 1590.39 1606.65 1623.83  1634.3 1648.55    1750
    7.79    7.79    7.29    6.99    7.39    7.83    7.78    7.25    7.25
                            5.99    6.39    6.83
BR Coef=-1 , 1 , 0 ,, 0 ,,,.8,0,0,0,
WSPro=,,,, 1 ,,,, 0 ,,,, 0 ,,,,-1 ,-1 ,-1 , 0 , 0 , 0 , 0 , 0
BC Design=,, 0 ,, 0 ,,,,,,
BC HTab HWMax=30.4

Type RM Length L Ch R = 1 ,6227.747,28,27.06,24.62
BEGIN DESCRIPTION:
copy of 441s1u ;  xs 2/4 Gravel Pit Road
Bank Station offset =      3403
Channel elevations adjusted based on slope between 441v7 and 441v8.  Right overbank not extended because flow from here down will not enter Jackson bayou again, but will flow directly into San Jacinto.  Block on left at watershed divide.  Cont/exp increased to lessen negative slope in profile.
END DESCRIPTION:
XS GIS Cut Line= 6
     3208426.264    13891983.711     3207503.808     13891823.65
     3207023.625    13892046.892     3206871.988     13892497.59
     3206820.614    13892567.472     3205743.137    13893618.017
#Sta/Elev= 30
       0   30.06   18.67   27.77   64.34   16.06   99.13   15.09   462.9    18.9
  605.07   13.13  829.26   13.16  997.93   15.97 1071.98   19.56 1097.18   24.24
 1128.44    25.5 1173.61   24.28 1221.51    13.6 1313.51   12.72 1379.27   16.21
 1590.52    4.52 1597.08   -4.23 1619.43     .39 1626.51    4.09 1837.69   11.01
 1949.03   20.96 2135.72   23.42 2566.75   17.62  2735.4    6.98 2863.47    7.52
 2922.35   11.62 2986.93    7.14 3188.47    9.78 3258.34   14.21  3534.5   13.61
#Mann= 5 ,-1 , 0
       0     .99       0 1128.44     .11       0 1590.52    .045       0
 1626.51     .11       0 2135.72     .99       0
#XS Ineff= 2 , 0
       0 1585.75    6.99    1630       0    7.25
Permanent Ineff=
       F       F
#Block Obstruct= 2 , 0
       0    1075      20    3533       0      20
Bank Sta=1590.52,1626.51
XS Rating Curve= 0
Exp/Cntr=.8,.6

Type RM Length L Ch R = 1 ,6200.685,394,432.89,433.53
BEGIN DESCRIPTION:
copy of 441s1u;  xs1/4 Gravel Pit Road
 - channel elevations adjusted based on slope between 441v7 and 441v8
Bank Station offset =      3374
Right overbank not extended because flow from here down will not enter Jackson bayou again, but will flow directly into San Jacinto.
END DESCRIPTION:
XS GIS Cut Line= 6
     3208413.628    13891912.104     3207444.838    13891789.952
     3207002.564    13892025.832     3206866.404    13892441.519
     3206811.022    13892522.861     3205654.682    13893651.714
#Sta/Elev= 30
       0   29.56   17.45   28.79   36.04   20.44   66.28   15.57  539.76   17.78
  617.44   13.68  831.23   13.43 1041.02   18.09 1071.95   24.55  1141.3   25.82
 1177.02   24.67 1229.25   14.05 1330.02   20.38 1462.95    9.45 1619.29    4.47
 1625.85   -4.28 1655.28    4.04 1841.52    9.86 1870.43    7.29 1941.39   10.71
  2028.8   21.99  2090.6   22.39 2536.69    7.58 2682.75    6.45 2899.61    7.85
  2935.2    12.9 3001.74    6.25 3250.34    9.13 3293.62   13.89  3630.7   13.59
#Mann= 5 ,-1 , 0
       0     .99       0 1330.02     .11       0 1619.29     .04       0
 1655.28     .11       0  2090.6     .99       0
#Block Obstruct= 2 , 0
       0    1055      20    3629       0      20
Bank Sta=1619.29,1655.28
XS Rating Curve= 0
Exp/Cntr=.3,.1

Type RM Length L Ch R = 1 ,5767.792,109.05,623.96,848.34
BEGIN DESCRIPTION:
441v7
Bank Station offset =      2986
Right overbank not extended because flow from here down will not enter Jackson bayou again, but will flow directly into San Jacinto.
Block in left overbank at watershed divide
END DESCRIPTION:
XS GIS Cut Line= 6
     3208381.405    13891770.551     3207513.045    13891652.924
     3206886.246    13891652.924     3206564.918    13891952.008
     3206444.544    13892367.525     3206109.977    13892651.752
#Sta/Elev= 30
       0   28.67    18.7   25.68   33.84   19.38   81.62   15.85  316.51   17.42
  408.38   13.55  637.89   19.47  701.53   13.14  991.42   13.83 1061.46   24.36
 1141.36    25.9 1206.57   19.84 1303.91       4 1550.57    5.37 1653.45   10.45
 1854.86     9.1 2008.98    3.94 2011.95    1.32 2013.67   -5.18 2039.74     .57
  2045.2    4.75 2125.81    5.69 2164.24    9.71 2334.42    6.02 2358.64    6.89
 2386.89   13.91 2435.95   14.99 2473.18   14.83 2514.63    6.34  2813.7    6.12
#Mann= 5 ,-1 , 0
       0     .99       0 1141.36     .11       0 2008.98     .04       0
  2045.2     .11       0 2435.95     .99       0
#Block Obstruct= 2 , 0
       0    1050      20    2812       0      20
Bank Sta=2008.98,2045.2
XS Rating Curve= 0
Exp/Cntr=.3,.1

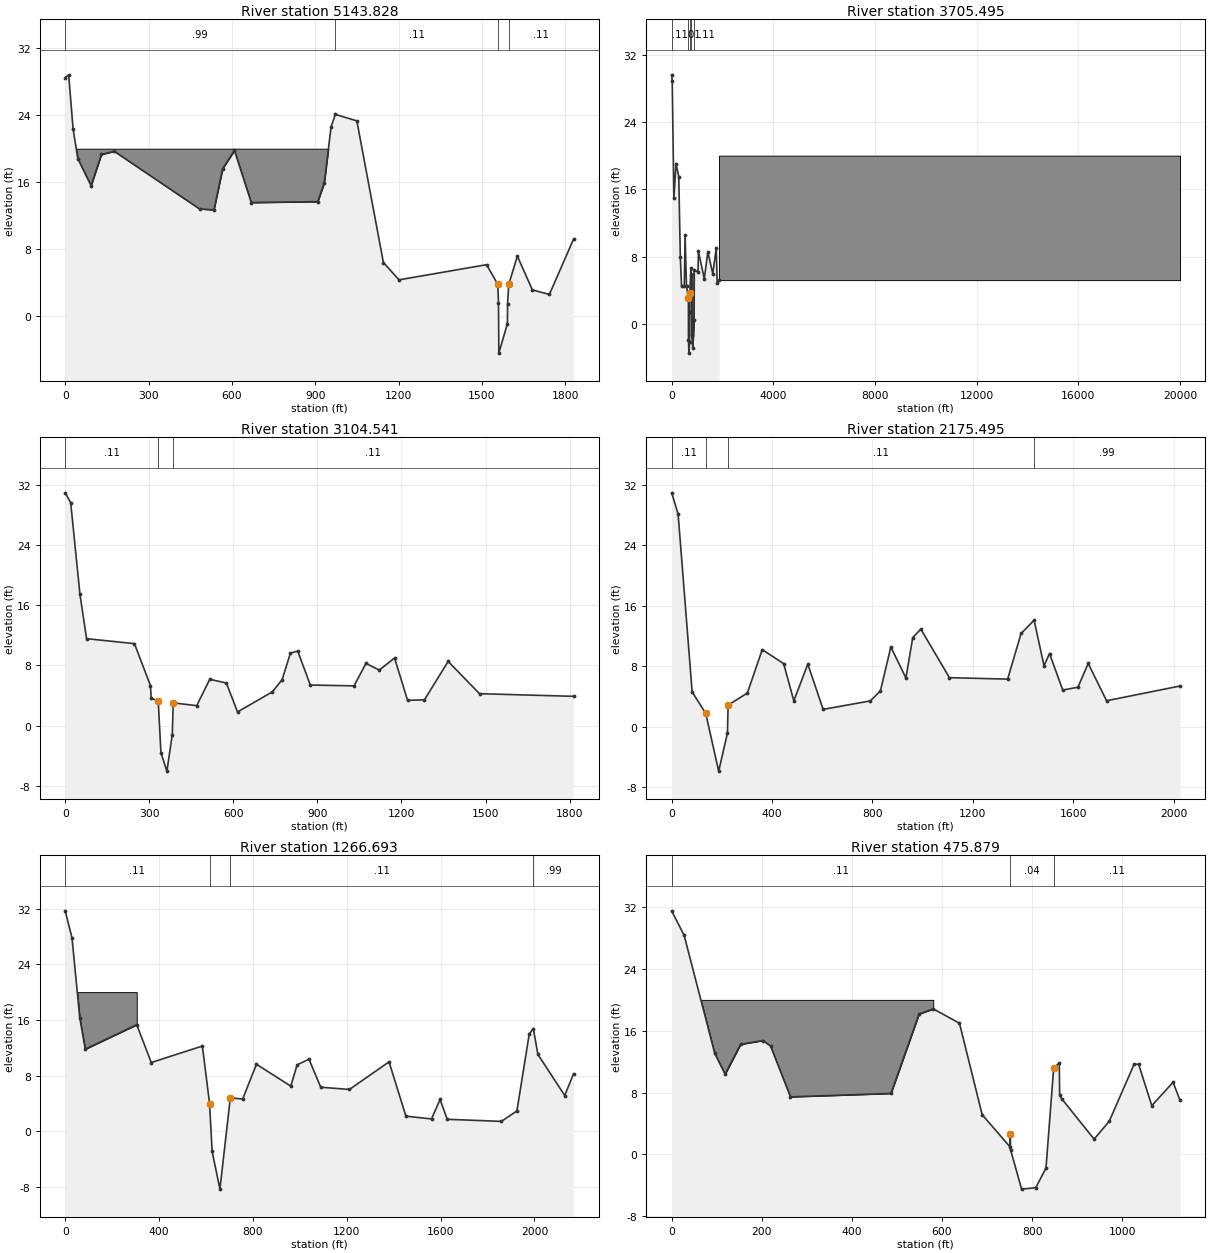
Type RM Length L Ch R = 1 ,5143.828,1036.03,1438.33,1283.29
BEGIN DESCRIPTION:
441v6
Bank Station offset =      3439
Right overbank not extended because flow from here down will not enter Jackson bayou again, but will flow directly into San Jacinto.
Block in left overbank at watershed divide
END DESCRIPTION:
XS GIS Cut Line= 6
     3208327.632    13891533.951     3207579.411    13891593.931
     3206855.471    13891570.118     3206793.284     13891548.02
     3206721.299    13891508.094        3206537.    13891415.651
#Sta/Elev= 30
       0   28.47   12.49   28.82   28.26    22.4   45.36   18.81   92.97   15.58
  130.18   19.31  176.57   19.69  483.33   12.81  535.24    12.7  566.57   17.62
     609   19.79   669.5   13.57  908.66   13.68  932.16   15.87  956.95   22.62
  972.28    24.1 1049.61   23.32 1145.11    6.41 1201.31    4.34 1516.42    6.15
 1556.86    3.81  1559.4    1.52 1560.62   -4.41 1591.52    -.88 1591.98    1.51
 1596.33     3.8  1627.3    7.17 1681.43    3.13 1742.64     2.6 1829.45     9.2
#Mann= 4 ,-1 , 0
       0     .99       0  972.28     .11       0 1556.86     .04       0
 1596.33     .11       0
#Block Obstruct= 2 , 0
       0     955      20    1828       0      20
Bank Sta=1556.86,1596.33
XS Rating Curve= 0
Exp/Cntr=.3,.1

Type RM Length L Ch R = 1 ,3705.495,696.41,600.95,428.64
BEGIN DESCRIPTION:
441v5
Bank Station offset =      4322
Right overbank not extended because flow from here down will not enter Jackson bayou again, but will flow directly into San Jacinto.
Block near channel is pond, so using 0.01 for Mannings n.
END DESCRIPTION:
XS GIS Cut Line= 5
     3208187.823    13890910.187     3207595.389    13890651.016
     3207354.871    13890572.171     3206957.292    13890535.584
     3206483.227    13890851.037
#Sta/Elev= 30
       0   29.61   21.78   28.86   87.27   14.94   170.9   19.06     279    17.5
  340.13    7.94  388.85    4.45  496.58    4.56  527.09   10.53  583.44     4.5
  657.69    3.07  660.51   -1.89  678.13   -3.48  704.72   -2.16  706.41    1.41
  711.83    3.72  761.32    6.59  779.54    5.83  788.34   -1.37  830.18   -2.82
  878.52     .41  883.86    6.36 1036.53    6.19 1052.43    8.61 1283.72    5.35
 1422.97    8.56 1617.03    5.97 1754.76    8.99  1790.8    4.86 1868.44     5.2
#Mann= 5 ,-1 , 0
       0     .11       0  657.69     .04       0  711.83     .11       0
  761.32     .01       0  883.86     .11       0
#Block Obstruct= 2 ,-1
     776     884       6    1860   20000      20
Bank Sta=657.69,711.83
XS Rating Curve= 0
Exp/Cntr=.3,.1

Type RM Length L Ch R = 1 ,3104.541,942.51,929.05,927.18
BEGIN DESCRIPTION:
441v4
Bank Station offset =      4637
Right overbanknot extended because flow from here down will not enter Jackson Bayou again, but will flow directly into San Jacinto.
END DESCRIPTION:
XS GIS Cut Line= 4
     3207961.322    13889947.224     3207675.029    13890049.988
     3207565.441     13890085.28     3206299.755    13890671.422
#Sta/Elev= 30
       0   30.93    19.6   29.63   52.56   17.45   76.28   11.55  247.09   10.89
  304.18    5.32  306.93    3.63  331.99    3.28  341.66    -3.6  362.88   -6.05
  382.17   -1.19  385.53    3.02  469.33    2.65  515.81    6.15  575.19    5.66
     615    1.81  739.32    4.49  774.06     6.1  803.69    9.63  829.89     9.9
  874.73    5.39 1030.82    5.28 1073.29    8.27 1120.76    7.38 1175.45    8.98
 1221.72    3.37 1281.91    3.41 1366.59    8.53 1478.66    4.24 1814.13    3.89
#Mann= 3 , 0 , 0
       0     .11       0  331.99     .04       0  385.53     .11       0
#Block Obstruct= 2 , 0
       0                    1813       0      20
Bank Sta=331.99,385.53
XS Rating Curve= 0
Exp/Cntr=.3,.1

Type RM Length L Ch R = 1 ,2175.495,1052.22,908.8,501.81
BEGIN DESCRIPTION:
441v3
Bank Station offset =      4813
Right overbank not extended because flow from here down will not enter Jackson Bayou again, but will flow directly into San Jacinto.
END DESCRIPTION:
XS GIS Cut Line= 5
     3207486.301     13889130.68     3207379.926     13889178.05
     3207270.147    13889217.741     3206876.314    13889385.335
     3206203.727    13890572.532
#Sta/Elev= 30
       0   30.93   25.65   28.13   81.59    4.62  135.72    1.78   187.3   -5.85
  222.34    -.81  224.85    2.87  301.62    4.47  360.93   10.21  446.21    8.36
  486.72    3.45  542.58    8.29  603.54    2.31  791.48    3.43  831.83    4.75
  873.38   10.56  933.49    6.46   960.7    11.8  992.77   12.92 1106.96     6.5
 1338.77    6.31 1392.38   12.34 1444.34    14.1 1483.74    8.07 1505.75    9.69
  1558.4    4.86 1618.99    5.24 1659.83    8.38 1733.06    3.45 2025.67     5.4
#Mann= 4 ,-1 , 0
       0     .11       0  135.72     .04       0  224.85     .11       0
 1444.34     .99       0
#Block Obstruct= 2 , 0
       0                    2006       0      20
Bank Sta=135.72,224.85
XS Rating Curve= 0
Exp/Cntr=.3,.1

Type RM Length L Ch R = 1 ,1266.693,670,790.81,900
BEGIN DESCRIPTION:
441v2
Cross section blocked on LOB at watershed boundary
Bank Station offset =      4341
Right overbank not extended because flow from here down will not enter Jackson Bayou again, but will flow directly into San Jacinto.
END DESCRIPTION:
XS GIS Cut Line= 6
     3206777.109    13888600.729     3206472.846    13888826.913
     3206530.949    13889038.469     3206560.017    13889144.357
      3206621.63    13889389.772     3206014.637    13890430.978
#Sta/Elev= 30
       0   31.69      29   27.81   61.97   16.33   85.31    11.8  304.86   15.32
  366.84    9.88  584.62   12.25  615.31    3.98  626.28   -2.91   659.4   -8.32
  703.72    4.79   756.5    4.64  815.21    9.63  961.48    6.49  988.42    9.55
 1039.06   10.36 1089.19    6.33  1211.4    6.01 1380.21    9.98 1452.18    2.17
 1561.25    1.77 1597.72    4.57 1628.34    1.72 1858.98    1.42 1925.24    2.92
 1977.95   14.01 1995.32   14.75 2014.57   11.05 2129.14    5.14 2166.57    8.26
#Mann= 4 ,-1 , 0
       0     .11       0  615.31     .04       0  703.72     .11       0
 1995.32     .99       0
#Block Obstruct= 2 , 0
       0  304.86      20    2164       0      20
Bank Sta=615.31,703.72
XS Rating Curve= 0
Exp/Cntr=.3,.1

Type RM Length L Ch R = 1 ,475.879 ,256,475.88,270
BEGIN DESCRIPTION:
441v1
Cross section blocked on LOB at watershed boundary
Bank Station offset =      4223
Right overbank not extended because flow from here down will not enter Jackson Bayou again, but will flow directly into San Jacinto.
END DESCRIPTION:
XS GIS Cut Line= 5
     3206586.961    13888517.645     3206259.826    13888767.987
     3205950.779    13888854.268     3205837.176     13888887.88
     3205573.228    13888971.393
#Sta/Elev= 30
       0   31.52   27.65   28.35   95.61   13.06  118.54   10.39  152.99   14.25
  202.51   14.74  219.39   14.03   263.6    7.45  486.64    7.89  548.93   18.16
  580.54   18.84  638.73   16.97   689.1    5.14  750.87     .98  751.32    2.64
  752.26     .58  776.54   -4.49   807.9   -4.31   830.7   -1.77  847.84   11.24
  860.23   11.81  861.03    7.72  865.31    7.22  937.53    1.98  971.16     4.3
 1026.42   11.69 1036.35   11.65 1065.56    6.31 1112.76    9.34 1128.11    7.01
#Mann= 3 , 0 , 0
       0     .11       0  751.32     .04       0  847.84     .11       0
#Block Obstruct= 2 , 0
       0  580.54      20    1126       0      20
Bank Sta=751.32,847.84
XS Rating Curve= 0
Exp/Cntr=.3,.1

Chan Stop Cuts=-1